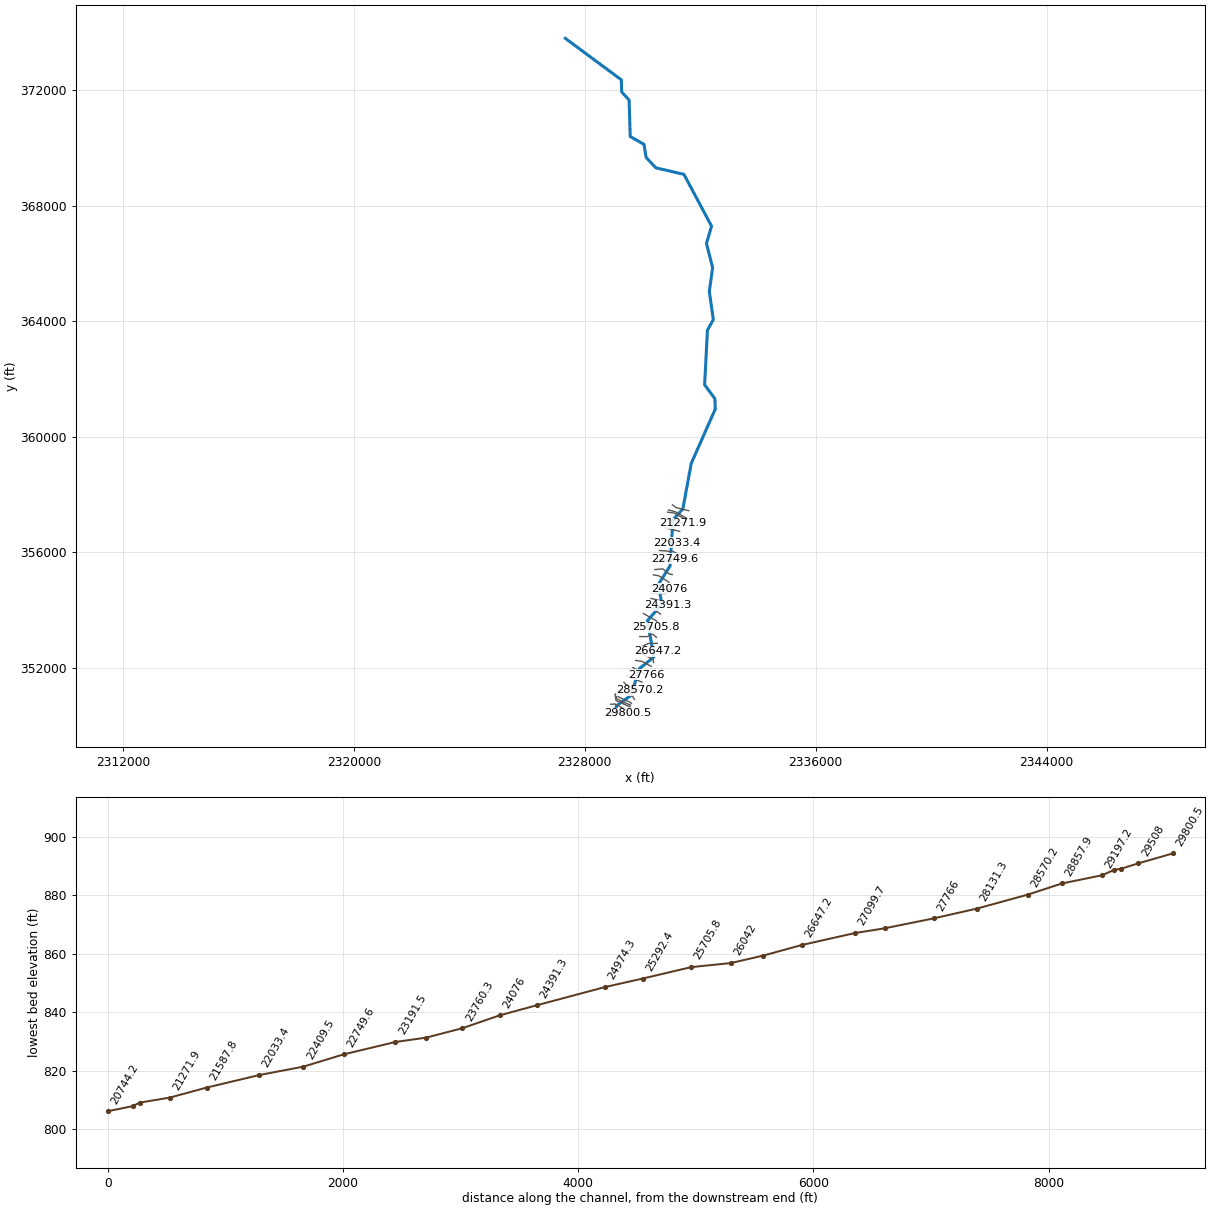
--- SFKSLPYCRK.prj (project) ---

Proj Title=SFKSLPYCRK
Current Plan=p01
Default Exp/Contr=0,0
English Units
Geom File=g01
Flow File=f01
Plan File=p01
BEGIN DESCRIPTION:
END DESCRIPTION:
DSS Export Rating Curves= 0
DSS Export Rating Curve Sorted= 0
DSS Export Volume Flow Curves= 0
DXF OffsetX= 0
DXF OffsetY= 0
DXF ScaleX= 0
DXF ScaleY= 0

--- SFKSLPYCRK.p01 (plan) ---

Plan Title=Floodplain
Program Version=4.00
Geom File=g01
Flow File=f01
K Sum by GR=0
Std Step Tol=0.01
Critical Tol=0.01
Num of Std Step Trials=20
Max Error Tol=0.3
Flow Tol Ratio=0.001
Split Flow NTrial=30
Split Flow Tol=0.02
Split Flow Ratio=0.02
Log Output Level=0
Friction Slope Method=1
Unsteady Friction Slope Method=2
Unsteady Bridges Friction Slope Method=1
Global Log Level=0
CheckData=False
Run HTab=0
Run UNet=0
Run PostProcess=0
UNET Theta=0
UNET Theta Warmup=0
UNET ZTol=0
UNET ZSATol=0
UNET MxIter=0
UNET MaxInSteps=0
UNET DtIC=0
UNET DtMin=0
UNET MaxCRTS=0
UNET WFStab=0
UNET SFStab=0
UNET WFX=0
UNET SFX=0
UNET DSS MLevel=0
UNET DZMax Abort=0
UNET Convert EG Bridges=0
UNET Use Existing IB Tables=0
UNET Froude Limit=0
UNET Froude Power=0
Write IC File=0
Echo Input=False
Echo Output=False
Write Detailed=0

--- SFKSLPYCRK.f01 (steady flow) ---

Flow Title=NFF Regression Equation
Program Version=4.00
Number of Profiles=1
Profile Names=P100yr
River Rch & RM=SFKSLPYCRK,Main      ,29800.5
508.9999
River Rch & RM=SFKSLPYCRK,Main      ,29508
510.5550
River Rch & RM=SFKSLPYCRK,Main      ,29197.2
588.1076
River Rch & RM=SFKSLPYCRK,Main      ,28570.2
708.6462
River Rch & RM=SFKSLPYCRK,Main      ,26042
735.6031
River Rch & RM=SFKSLPYCRK,Main      ,25705.8
852.0655
River Rch & RM=SFKSLPYCRK,Main      ,23760.3
945.9214
River Rch & RM=SFKSLPYCRK,Main      ,21587.8
1048.244
River Rch & RM=SFKSLPYCRK,Main      ,20410
1157.097
River Rch & RM=SFKSLPYCRK,Main      ,18645.3
1251.414
River Rch & RM=SFKSLPYCRK,Main      ,17467.2
1363.427
River Rch & RM=SFKSLPYCRK,Main      ,14226.7
1454.176
River Rch & RM=SFKSLPYCRK,Main      ,13586.7
1570.567
River Rch & RM=SFKSLPYCRK,Main      ,10754.1
1726.340
River Rch & RM=SFKSLPYCRK,Main      ,7655
1857.303
River Rch & RM=SFKSLPYCRK,Main      ,7325.8
2243.161
River Rch & RM=SFKSLPYCRK,Main      ,435.2
2423.395
River Rch & RM=SFKSLPYCRK,Main      ,121.4
2424.456
Boundary for River Rch & Prof#=SFKSLPYCRK,Main      ,1
Up Type=0
Dn Type=3
Dn Slope=0.005318

--- SFKSLPYCRK.g01 (geometry) ---

Geom Title=USGS 10m DEM
Program Version=4.10

River Reach=SFKSLPYCRK      ,Main
Reach XY= 30
     2329080.798      350427.853     2329091.215      350684.798
     2329605.104       351054.59     2329884.618       351969.52
     2330396.771      352382.714     2330167.604      353634.451
     2330664.132      354198.687     2330559.965      354910.492
     2330954.062      355530.284     2331053.021      357130.978
     2331395.534      357502.638     2331688.438      359082.367
     2332518.298      360957.367     2332507.882      361320.214
     2332150.243      361801.117     2332249.201      363691.742
     2332452.326      364059.798     2332313.437       365032.02
     2332428.021      365858.409     2332214.653      366691.048
        2332390.      367293.478     2331435.139      369085.145
     2330462.982      369310.363     2330122.639      369670.214
     2330053.194      370123.339     2329574.028      370394.173
     2329535.833      371658.062     2329278.889      371935.839
        2329265.      372357.715     2327324.877       373793.63

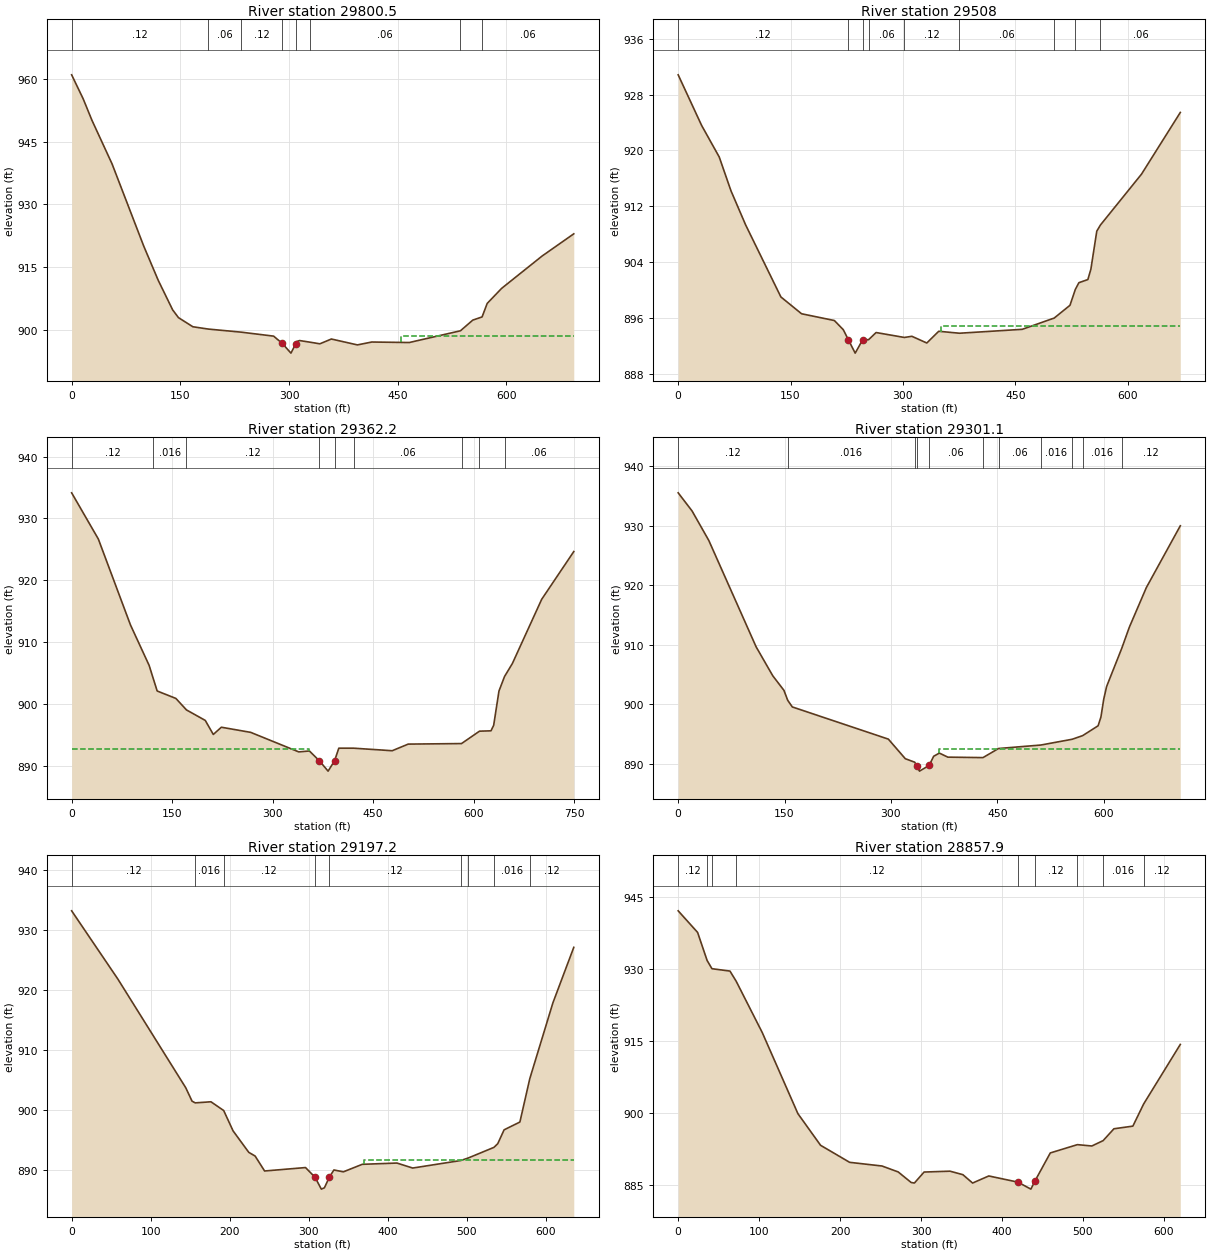
Type RM Length L Ch R = 1 ,29800.5 ,303.3,292.5,285
XS GIS Cut Line= 2
     2328781.463      350442.132     2329474.542      350437.711
#Sta/Elev= 30
       0  961.02    15.9  955.28    27.9  950.18    55.8  939.68    99.6  919.95
   119.5   911.8   139.4  904.72   147.4  902.86   167.3  900.67  188.49900.1152
  234.33899.3684   278.8  898.42   290.8  896.66   302.7  894.35  309.36  896.58
   310.7  897.13   314.7  897.36  329.26896.9668   342.6  896.58   358.5  897.73
   394.4  896.32   414.3  897.01     466  896.89  536.63899.6989   553.7  902.26
  566.53903.0211   573.6  906.26   593.5  909.86   649.3   917.6   693.1  922.93
#Mann= 8 ,-1 , 0
       0     .12       0  188.49     .06       0  234.33     .12       0
   290.8    .045       0  309.36     .12       0  329.26     .06       0
  536.63    .016       0  566.53     .06       0
#XS Ineff= 2 , 0
                          454.39          898.38
Permanent Ineff=
       F       F
Bank Sta=290.8,309.36
XS Rating Curve= 0 ,0
Exp/Cntr=0.3,0.1

Type RM Length L Ch R = 1 ,29508   ,144.5,145.8,143.7
XS GIS Cut Line= 3
     2328896.345      350743.695     2329052.797      350752.779
     2329501.853      350503.546
#Sta/Elev= 30
       0  930.84    31.3  923.59    54.8  919.07    70.5  914.22    90.1  909.33
   137.1  899.02   164.7  896.61   208.5  895.64   220.4  894.33   227.2  892.88
   236.3  890.97  246.37   892.9  254.17892.8929   264.2  893.92  301.87893.2153
     312  893.38   331.9  892.42   347.8   894.1   375.5 893.821   459.3  894.38
  501.95 895.994     523  897.82  530.17900.0927   534.9  901.06   546.9  901.51
   550.9  902.98   558.8  908.44  563.63909.3183   618.5  916.61   670.3  925.45
#Mann= 9 ,-1 , 0
       0     .12       0   227.2    .045       0  246.37     .12       0
  254.17     .06       0  301.87     .12       0   375.5     .06       0
  501.95     .12       0  530.17    .016       0  563.63     .06       0
#XS Ineff= 2 , 0
                          351.08           894.9
Permanent Ineff=
       F       F
Bank Sta=227.2,246.37
XS Rating Curve= 0 ,0
Exp/Cntr=0.3,0.1

Type RM Length L Ch R = 1 ,29362.2 ,61.2,61.2,61.3
XS GIS Cut Line= 3
     2329047.589      351089.585     2329084.047      350869.099
     2329564.313      350654.107
#Sta/Elev= 30
       0  934.14    39.9  926.66    87.8  912.78   115.7  906.23  121.63904.1769
   127.7  902.09   155.6  900.89   171.4899.0335   199.5  897.33   211.5  895.06
   223.5  896.23   267.3   895.4   339.1  892.24     355  892.39     370890.7825
   382.9  889.13   392.5   890.8   398.9  892.84  420.89892.8405   478.6  892.43
   502.5   893.5  582.09893.5867  608.93895.5917   626.1  895.65   630.1  896.54
     638  902.08   646.3904.4295     658  906.53   701.8  916.92   749.7  924.64
#Mann= 9 ,-1 , 0
       0     .12       0  121.63    .016       0   171.4     .12       0
     370    .045       0   392.5     .12       0  420.89     .06       0
  582.09     .12       0  608.93    .016       0   646.3     .06       0
#XS Ineff= 2 , 0
          355.01  892.77
Permanent Ineff=
       F       F
Bank Sta=370,392.5
XS Rating Curve= 0 ,0
Exp/Cntr=0.3,0.1

Type RM Length L Ch R = 1 ,29301.1 ,103.1,103.9,104.2
XS GIS Cut Line= 3
     2329082.022      351108.624     2329113.561      350922.918
     2329587.765      350710.639
#Sta/Elev= 30
       0   935.5    19.6  932.45    43.2  927.49   109.9  909.61   133.4  904.74
   149.1   902.3  154.39900.6378   160.9  899.51   296.3   894.1   320.2  890.81
  333.47890.2196   336.2  889.66   340.2  888.72  353.84  889.68   360.2  891.22
   368.2  891.75   380.2  891.07  429.74890.9932  451.64892.5216  511.23893.1048
  555.32 894.073  570.21 894.685     592  896.34     596  897.82     600  900.85
     604  902.94  625.41909.3806     636   912.9     660  919.57   707.9  929.96
#Mann= 11 ,-1 , 0
       0     .12       0  154.39    .016       0  333.47     .06       0
   336.2    .045       0  353.84     .06       0  429.74    .016       0
  451.64     .06       0  511.23    .016       0  555.32     .12       0
  570.21    .016       0  625.41     .12       0
#XS Ineff= 2 , 0
                          368.21          892.47
Permanent Ineff=
       F       F
Bank Sta=336.2,353.84
XS Rating Curve= 0 ,0
Exp/Cntr=0.3,0.1

Type RM Length L Ch R = 1 ,29197.2 ,338.1,339.3,338.8
XS GIS Cut Line= 4
     2329137.577       351128.59     2329168.827      350995.777
     2329561.189      350817.826      2329614.62      350775.373
#Sta/Elev= 30
       0  933.18    58.5  921.82   144.4  903.73   152.4  901.49  156.42901.2106
   176.3  901.39  192.43899.9349   204.3  896.55   224.2  892.97   232.2  892.36
   244.2  889.87     296  890.44     308  888.83     316  886.85   319.9  887.07
  326.06  888.82   331.9  890.04   343.9  889.73   367.8  890.98   411.7  891.19
   431.6  890.36  492.69891.6176  502.22892.0475   534.4893.7975   539.3  894.42
   547.3  896.72   567.3  898.02   579.8905.2221     609  917.83   635.5   927.1
#Mann= 9 ,-1 , 0
       0     .12       0  156.42    .016       0  192.43     .12       0
     308    .045       0  326.06     .12       0  492.69     .06       0
  502.22     .12       0   534.4    .016       0   579.8     .12       0
#XS Ineff= 2 , 0
                          369.87          891.66
Permanent Ineff=
       F       F
Bank Sta=308,326.06
XS Rating Curve= 0 ,0
Exp/Cntr=0.3,0.1

Type RM Length L Ch R = 1 ,28857.9 ,287,287.7,287.8
XS GIS Cut Line= 3
     2329203.996      351221.445     2329647.283      351028.036
     2329721.432      350913.292
#Sta/Elev= 30
       0  942.21      24   937.7   35.77931.8305   41.73930.1192      64  929.62
    71.7927.4883   103.9  916.77   147.9  899.84   175.9  893.23   211.8  889.67
   251.8   888.9   271.8  887.66   287.8  885.46   291.8  885.34   303.8  887.64
   335.8  887.82   351.7  887.09   363.7  885.34   383.7  886.82   419.7  885.53
   435.7  884.07   440.8  885.79   459.7  891.63  493.19893.3637     511  893.08
  524.99894.2058   538.3  896.68   561.7  897.23  575.03901.8657   620.3   914.3
#Mann= 9 ,-1 , 0
       0     .12       0   35.77     .08       0   41.73    .016       0
    71.7     .12       0   419.7    .045       0   440.8     .12       0
  493.19     .06       0  524.99    .016       0  575.03     .12       0
Bank Sta=419.7,440.8
XS Rating Curve= 0 ,0
Exp/Cntr=0.3,0.1

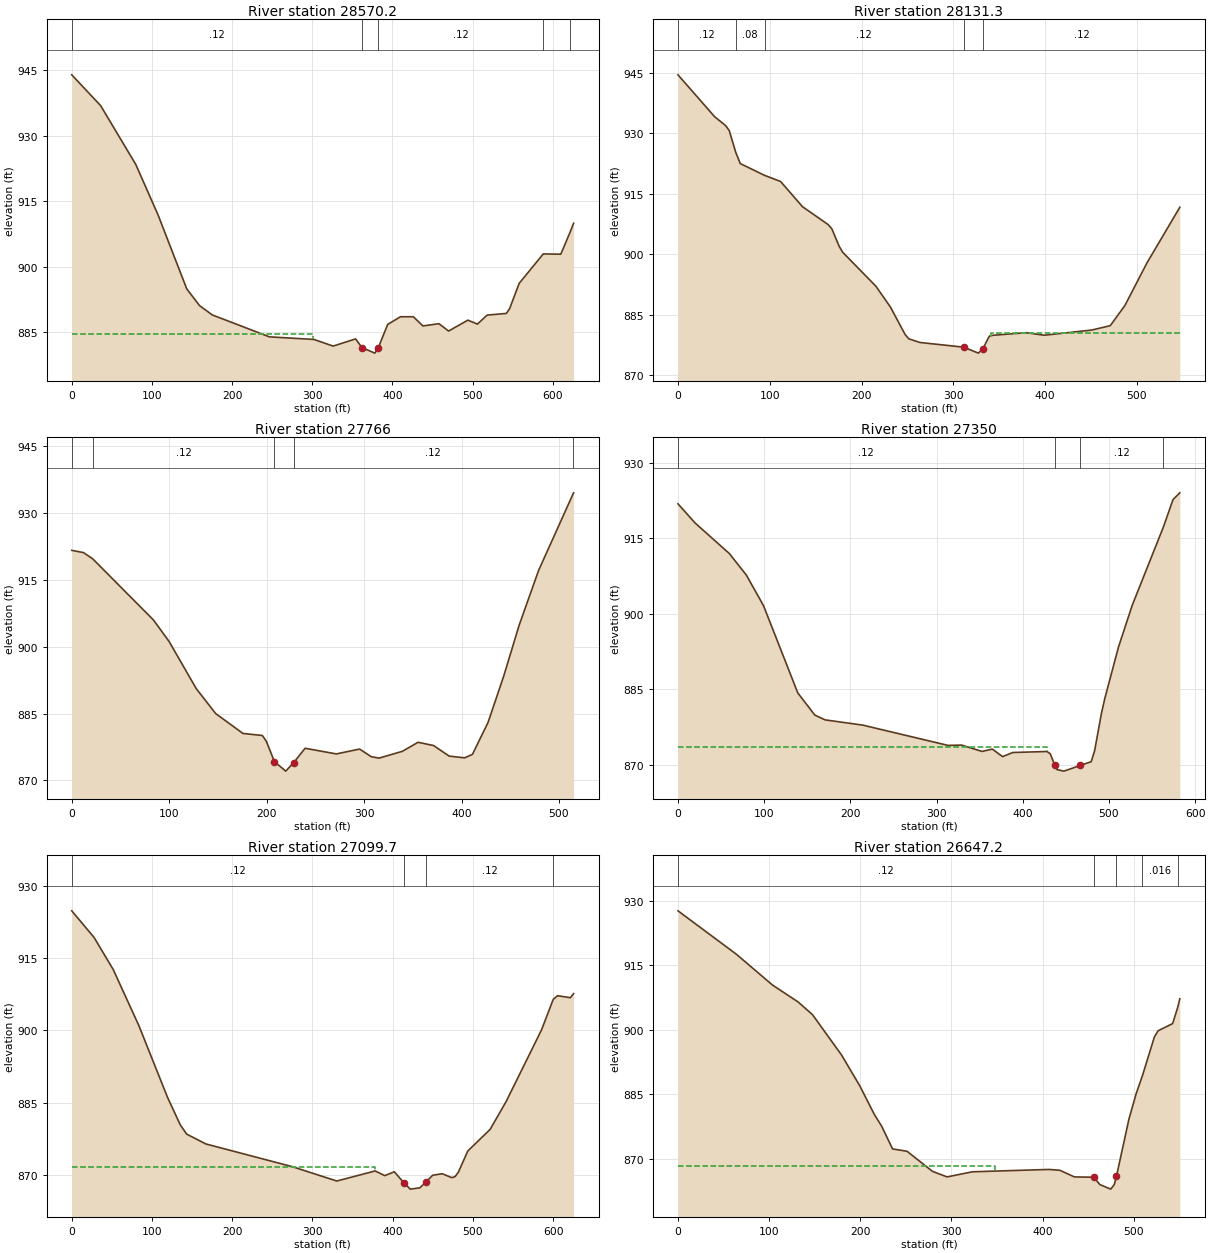
Type RM Length L Ch R = 1 ,28570.2 ,443,438.9,421.6
XS GIS Cut Line= 4
     2329355.546      351504.437     2329418.193      351431.845
     2329602.332      351348.412     2329905.416      351223.331
#Sta/Elev= 30
       0  943.91      36  936.87    79.9   923.4   107.8   911.8   143.4  894.97
   159.3  891.15   175.2  889.01   246.5  883.99     302   883.4     326  881.88
     354  883.52     362  881.53     378  880.27     382  881.36     394  886.83
     410  888.59     426  888.59     438  886.49     458     887     470  885.32
     494  887.81     506  886.91     518  888.96     542  889.35     546   890.4
     558  896.22  588.06902.9578   609.9  902.89  621.37 907.855   625.9  909.98
#Mann= 5 ,-1 , 0
       0     .12       0     362    .045       0     382     .12       0
  588.06    .016       0  621.37     .12       0
#XS Ineff= 2 , 0
          301.24  884.61
Permanent Ineff=
       F       F
Bank Sta=362,382
XS Rating Curve= 0 ,0
Exp/Cntr=0.3,0.1

Type RM Length L Ch R = 1 ,28131.3 ,357.8,365.3,364
XS GIS Cut Line= 2
      2329476.64      351720.583     2329981.028      351509.087
#Sta/Elev= 30
       0  944.54    39.9  934.15    51.9  931.94    55.9  930.68   62.99925.2681
    67.9   922.5   94.31919.5727   111.8  918.06   135.7  911.79   163.7  907.34
   167.7   906.3   175.7  901.93   179.6  900.45   215.6  892.06   231.6  886.84
   247.5  880.06   251.5  878.98   263.5  878.07   311.4   876.9   327.4  875.42
   332.4  876.55   339.3  879.64   343.3  879.85   379.3  880.49   399.2  879.86
   451.1  881.16   471.1  882.24     487  887.23     511  897.79   546.9  911.65
#Mann= 5 ,-1 , 0
       0     .12       0   62.99     .08       0   94.31     .12       0
   311.4    .045       0   332.4     .12       0
#XS Ineff= 2 , 0
                          341.18          880.54
Permanent Ineff=
       F       F
Bank Sta=311.4,332.4
XS Rating Curve= 0 ,0
Exp/Cntr=0.3,0.1

Type RM Length L Ch R = 1 ,27766   ,416.2,416,415.7
XS GIS Cut Line= 2
     2329665.442      352016.156     2330118.567      351771.365
#Sta/Elev= 30
       0  921.61      12  921.11   21.45919.7209    83.8     906    99.8   901.2
   127.8  890.58   147.7     885   175.7  880.54   195.6  880.08   199.6  878.82
     208  874.22   219.6  872.09   227.6  873.97   239.5  877.22   271.5  875.95
   295.4  877.04   307.4  875.32   315.4  875.01   339.4  876.54   355.3  878.56
   371.3  877.83   387.3  875.46   403.2  875.07   411.2  875.85   427.2  883.01
   443.2  893.35   459.1  904.81   479.1  917.11  514.44934.2636     515  934.51
#Mann= 5 ,-1 , 0
       0    .016       0   21.45     .12       0     208    .045       0
   227.6     .12       0  514.44    .016       0
Bank Sta=208,227.6
XS Rating Curve= 0 ,0
Exp/Cntr=0.3,0.1

Type RM Length L Ch R = 1 ,27350   ,249.5,250.4,250.8
XS GIS Cut Line= 3
     2329761.796      352259.646     2329985.754      352227.094
     2330298.254      352056.521
#Sta/Elev= 30
       0   921.8    19.8     918    59.6  911.92    79.4  907.63    99.3  901.55
     139  884.24   158.8  879.83   170.7  878.88   214.4  877.84   313.3  873.81
   329.2  873.87   352.9  872.61   364.8  873.08   376.6  871.58   388.5   872.4
   428.1   872.6     432  872.14   436.9870.0077   439.9     869   447.8   868.7
   466.9 869.831   479.5  870.58   483.4  872.73   491.4  880.21   495.3  883.16
   511.1  893.33     527  901.61  563.31917.2231   574.4  922.64   582.3  923.98
#Mann= 4 ,-1 , 0
       0     .12       0   436.9    .045       0   466.9     .12       0
  563.31    .016       0
#XS Ineff= 2 , 0
          427.86  873.48
Permanent Ineff=
       F       F
Bank Sta=436.9,466.9
XS Rating Curve= 0 ,0
Exp/Cntr=0.3,0.1

Type RM Length L Ch R = 1 ,27099.7 ,443.1,452.5,461.6
XS GIS Cut Line= 3
     2329906.327      352526.573     2330365.963      352297.406
      2330382.89      352186.729
#Sta/Elev= 30
       0  924.82    27.9  919.28    51.8  912.61    83.6  901.03   119.4  886.12
   135.4  880.39   143.3   878.5   167.2  876.46   274.7  871.76   330.4  868.77
   378.2  870.86   390.2  869.89   402.1  870.69   414.1  868.39     422  867.09
     434  867.36   441.9  868.63   449.9  869.97   461.8  870.28   473.8  869.47
   477.8  869.69   481.8  870.56   493.7     875   521.6  879.49   541.6   885.3
   585.6  900.12  600.23906.4647   605.6  907.21   621.6   906.8   625.6  907.65
#Mann= 4 ,-1 , 0
       0     .12       0   414.1    .045       0   441.9     .12       0
  600.23    .016       0
#XS Ineff= 2 , 0
          377.81  871.59
Permanent Ineff=
       F       F
Bank Sta=414.1,441.9
XS Rating Curve= 0 ,0
Exp/Cntr=0.3,0.1

Type RM Length L Ch R = 1 ,26647.2 ,331.8,334.1,336
XS GIS Cut Line= 2
      2329976.64      352633.344     2330524.817      352582.562
#Sta/Elev= 30
       0  927.64    63.8   917.6   103.7   910.4   131.6   906.5   147.6  903.52
   179.5  894.13   199.5  886.97   215.4  880.34   223.4  877.63   235.4  872.34
   251.3  871.79   279.2  867.12   295.2  865.84   323.1  867.03   406.9  867.57
   418.9  867.38   434.8  865.84   456.1865.7578   462.8  864.06   474.7     863
   478.6  864.06  480.95  865.94   494.7  879.28   502.6  885.16  509.46 889.333
   522.6  898.35   526.6  899.77   542.6  901.45  548.17905.2045   550.5  907.22
#Mann= 5 ,-1 , 0
       0     .12       0   456.1    .045       0  480.95     .12       0
  509.46    .016       0  548.17     .12       0
#XS Ineff= 2 , 0
          347.99  868.28
Permanent Ineff=
       F       F
Bank Sta=456.1,480.95
XS Rating Curve= 0 ,0
Exp/Cntr=0.3,0.1

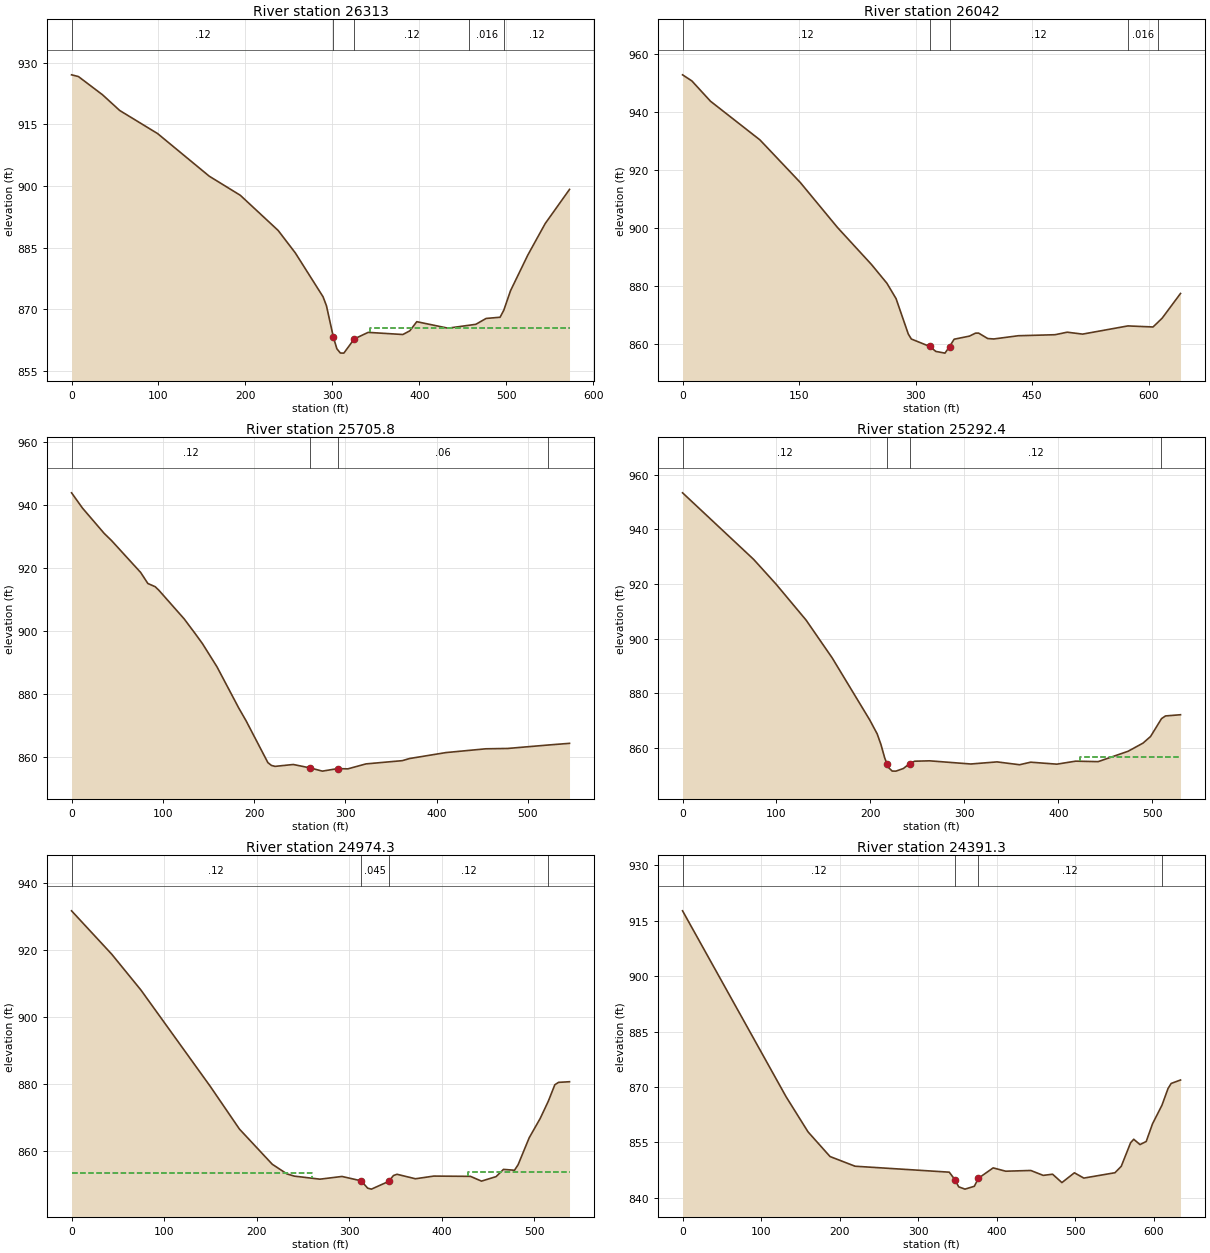
Type RM Length L Ch R = 1 ,26313   ,260.7,271.1,281.4
XS GIS Cut Line= 3
     2329961.015      352736.208     2330209.713       352849.49
     2330509.192      352852.094
#Sta/Elev= 30
       0  927.03     7.9  926.61    35.6  922.18    55.4  918.35      99  912.73
   158.4  902.36   194.1  897.72   237.6  889.17   257.4  883.69   289.3  873.02
   293.2  870.84   301.2  863.18   305.2  860.36   309.2  859.34   313.2  859.31
   325.2  862.77   341.2  864.36   381.1  863.84   389.1  864.74   397.1  866.96
     433  865.38  457.45866.0979     465  866.32   476.9  867.75   492.9  868.04
  497.21869.7609   504.9  874.48   524.8  883.16   544.8  890.83   572.8  899.15
#Mann= 5 ,-1 , 0
       0     .12       0   301.2    .045       0   325.2     .12       0
  457.45    .016       0  497.21     .12       0
#XS Ineff= 2 , 0
                          343.03          865.54
Permanent Ineff=
       F       F
Bank Sta=301.2,325.2
XS Rating Curve= 0 ,0
Exp/Cntr=0.3,0.1

Type RM Length L Ch R = 1 ,26042   ,347.5,336.1,321.9
XS GIS Cut Line= 4
     2329905.025      353086.469     2330156.327      353083.865
     2330345.129      353172.406     2330485.754      353057.823
#Sta/Elev= 30
       0  952.67      12  950.57    35.9  943.59    99.7  930.24   151.6  915.58
   199.5  900.08   243.3  887.32   263.1  880.88   274.9  875.59   290.7  863.36
   294.6  861.66   318.2  859.11   326.1  857.39   337.9   856.8  343.77  859.06
   349.7  861.59   369.4  862.66   377.2  863.68   381.2   863.7     393  861.82
   400.8  861.68   432.3  862.79   479.6  863.14   495.3  864.01   515.1  863.35
  573.43866.1724   605.8  865.81  612.09867.4193   617.6  868.86   641.2  877.35
#Mann= 5 ,-1 , 0
       0     .12       0   318.2    .045       0  343.77     .12       0
  573.43    .016       0  612.09     .12       0
Bank Sta=318.2,343.77
XS Rating Curve= 0 ,0
Exp/Cntr=0.3,0.1

Type RM Length L Ch R = 1 ,25705.8 ,425.4,413.5,400.6
XS GIS Cut Line= 2
     2329908.932        353418.5     2330454.504      353410.687
#Sta/Elev= 30
       0  943.91      12  939.04    35.8  930.99    43.8  928.73    75.7  918.59
    83.6  915.08    91.6  914.06    95.6  912.95   123.5  903.78   135.4  899.16
   143.4  895.96   159.3   888.6   183.2  875.47   191.2  871.43   215.1  858.12
     219  857.22     223  856.92   242.9  857.52   261.6856.4177   274.8  855.41
   291.6 856.211   302.7  856.13   322.6  857.71   362.4  858.74   370.4  859.42
   410.2  861.31     454  862.51   477.9  862.62  521.99863.7073   545.6  864.25
#Mann= 4 ,-1 , 0
       0     .12       0   261.6    .045       0   291.6     .06       0
  521.99     .12       0
Bank Sta=261.6,291.6
XS Rating Curve= 0 ,0
Exp/Cntr=0.3,0.1

Type RM Length L Ch R = 1 ,25292.4 ,320.8,318.1,315.7
XS GIS Cut Line= 2
     2330027.421      353885.948     2330488.359      353624.229
#Sta/Elev= 30
       0  953.35    75.7  928.98    99.6   919.9   131.5  906.77   159.4  892.87
   199.3   870.2   207.2  865.11   211.2  861.23   215.2  856.31   217.8  854.04
   219.1  852.83   223.2  851.51   227.2  851.49   235.1  852.46   241.6854.2225
   247.1  855.12     263  855.26   306.9   854.1   334.8  854.87   358.7  853.83
   370.6  854.76   398.5  854.04   418.5  855.14   442.4  854.96   474.3  858.76
   490.2  861.75   498.2  864.16  509.85870.6931   514.1  871.69   530.1  872.13
#Mann= 4 ,-1 , 0
       0     .12       0   217.8    .045       0   241.6     .12       0
  509.85    .016       0
#XS Ineff= 2 , 0
                          423.53          856.82
Permanent Ineff=
       F       F
Bank Sta=217.8,241.6
XS Rating Curve= 0 ,0
Exp/Cntr=0.3,0.1

Type RM Length L Ch R = 1 ,24974.3 ,573.2,583,588.7
XS GIS Cut Line= 3
     2330158.932      354116.417     2330365.963      354051.312
     2330625.077      353861.208
#Sta/Elev= 30
       0  931.62    43.4  918.69      75  907.99     150  879.24   181.5  866.52
     217  856.02   232.9  853.14   240.8  852.48   268.6  851.57   292.4  852.38
     313 851.082   320.2  848.88   324.2   848.6     343850.9175     348  852.65
   351.9  853.03   371.8  851.69   391.6  852.49   431.3  852.41   443.2  850.99
     459  852.33     467  854.49   478.9  854.23   482.8  855.87   494.8  863.92
   506.7  869.69  515.52874.8593   522.5  879.73   526.5  880.45   538.4  880.64
#Mann= 4 ,-1 , 0
       0     .12       0     313    .045       0     343     .12       0
  515.52    .016       0
#XS Ineff= 2 , 0
          260.06  853.51  428.48          853.68
Permanent Ineff=
       F       F
Bank Sta=313,343
XS Rating Curve= 0 ,0
Exp/Cntr=0.3,0.1

Type RM Length L Ch R = 1 ,24391.3 ,309.6,315.3,320.6
XS GIS Cut Line= 3
     2330294.348      354408.083       2330701.9      354307.823
     2330868.567      354172.406
#Sta/Elev= 30
       0  917.67   131.9  867.34   159.9  857.82   187.9  851.15   219.8  848.53
   339.8  846.92     347 844.888   351.8  842.95   359.8  842.33   371.7   843.1
     377845.2863   395.7  848.08   411.7  847.18   443.6  847.38   459.5  846.05
   471.4  846.37   483.3   844.1   499.2  846.75   511.2  845.32   550.9  846.77
   558.9  848.51   570.8  854.88   574.8  855.83   582.8  854.39   590.7  855.23
   598.7     860  610.81865.0697   618.5  869.57   622.5  870.94   634.4  871.87
#Mann= 4 ,-1 , 0
       0     .12       0     347    .045       0     377     .12       0
  610.81    .016       0
Bank Sta=347,377
XS Rating Curve= 0 ,0
Exp/Cntr=0.3,0.1

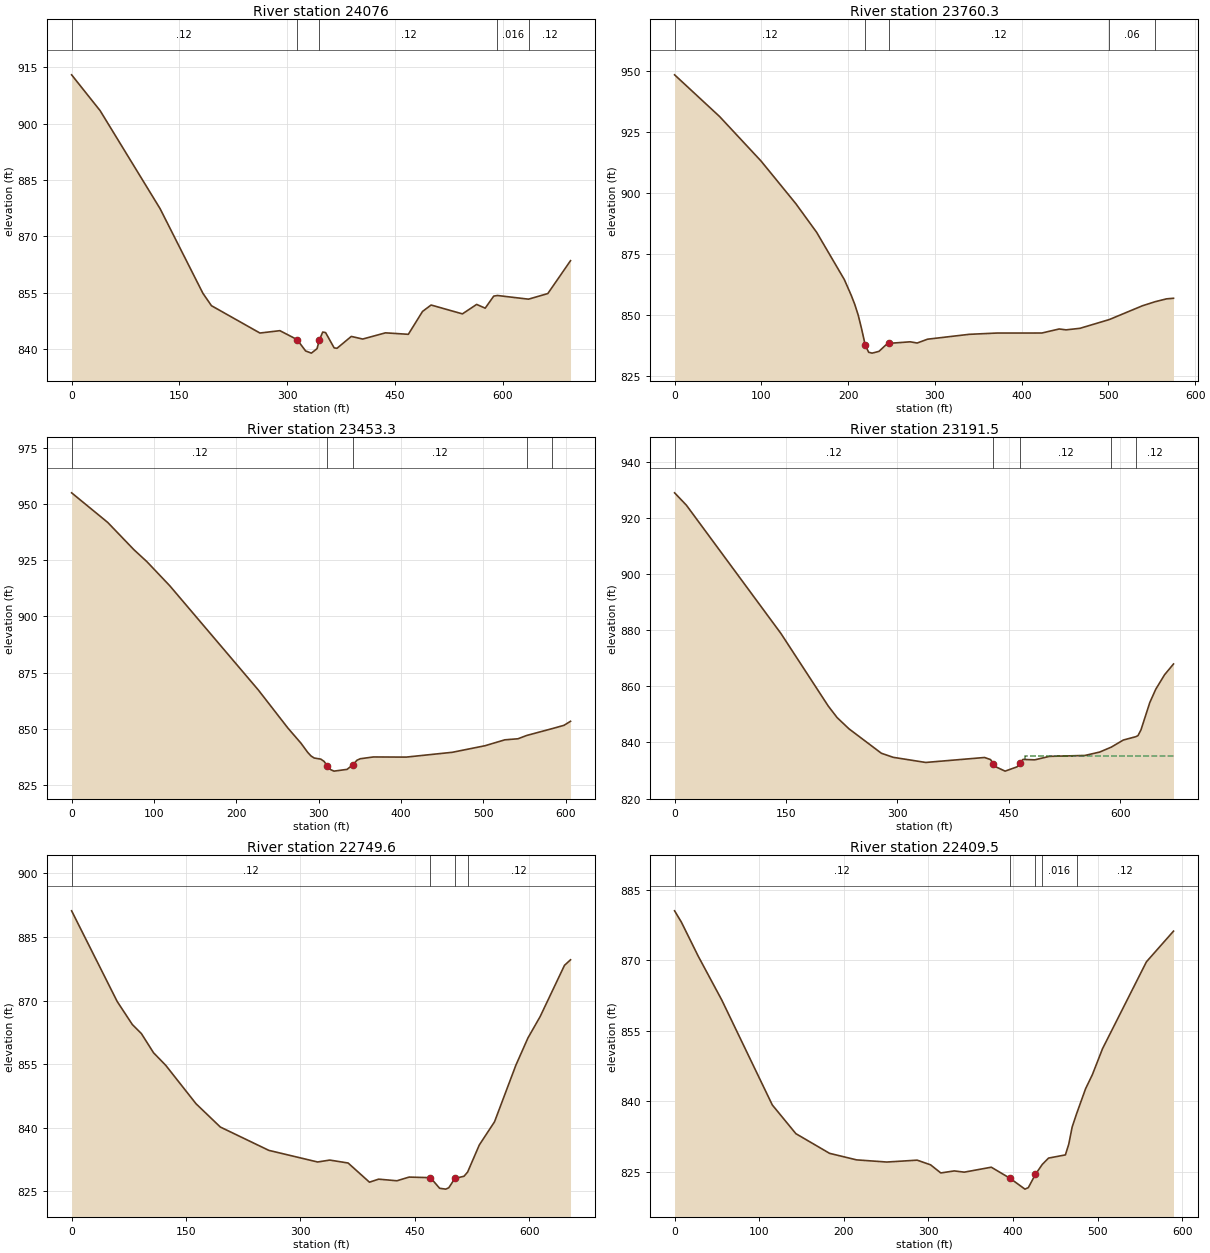
Type RM Length L Ch R = 1 ,24076   ,315.4,315.7,315.4
XS GIS Cut Line= 3
     2330319.088      354583.865     2330787.838       354574.75
     2330940.182      354741.417
#Sta/Elev= 30
       0  912.98    39.7  903.44   123.2  877.34   182.8  854.81   194.7  851.51
   262.2  844.23     290  844.86   313.9  842.49   325.8  839.46   333.8  838.88
   341.7  840.07  344.95  842.38   349.6  844.49   353.6  844.35   365.5  840.28
   369.5  840.17   389.4  843.33   405.3  842.63     437  844.28   468.8  843.89
   488.6  849.99   500.5  851.69   544.1  849.33   563.9  851.85   575.8  850.85
   587.7  854.06  592.92854.2237   636.1853.2468     663  854.74   694.6  863.49
#Mann= 5 ,-1 , 0
       0     .12       0   313.9    .045       0  344.95     .12       0
  592.92    .016       0   636.1     .12       0
Bank Sta=313.9,344.95
XS Rating Curve= 0 ,0
Exp/Cntr=0.3,0.1

Type RM Length L Ch R = 1 ,23760.3 ,319.6,307,294.2
XS GIS Cut Line= 2
     2330324.296      354846.885     2330899.426      354847.005
#Sta/Elev= 30
       0  948.57    51.9  931.47    99.8  913.18   139.8  895.74   163.8  883.99
   195.7  864.63   203.7  858.13   207.7  854.46   211.7  850.03   215.7  844.26
   219.7  837.88   223.7  834.85   227.7   834.5   235.6  835.22   243.6  837.87
   247.6  838.51   271.6  839.14   279.6  838.64   291.6  840.21   339.5   842.2
   371.4  842.73   423.4  842.74   443.3   844.4   451.3  844.04   467.3  844.67
  501.07848.2557   539.2   853.9  553.81855.5614   567.1  856.75   575.1  856.98
#Mann= 5 ,-1 , 0
       0     .12       0   219.7    .045       0   247.6     .12       0
  501.07     .06       0  553.81    .016       0
Bank Sta=219.7,247.6
XS Rating Curve= 0 ,0
Exp/Cntr=0.3,0.1

Type RM Length L Ch R = 1 ,23453.3 ,264.2,261.8,259.5
XS GIS Cut Line= 3
     2330377.682      355223.187     2330565.437      355188.437
       2330916.5      354967.448
#Sta/Elev= 30
       0  954.87    43.8  941.74    75.6  929.63    91.5  924.27   119.3  913.55
   226.8  867.27   262.7  850.37   278.7  843.59   286.7  839.59   290.7     838
   294.6  837.09   302.6   836.6   306.6  835.58   310.6   833.5   314.6  831.92
   318.6  831.27   334.5  832.05   341.7 834.148   346.5  836.11   350.5  836.77
   366.4  837.56   406.3   837.5   462.2  839.63   502.1  842.56     526  845.17
     542  845.64  552.53847.1011   583.9850.1852   597.8   851.6   605.8   853.4
#Mann= 5 ,-1 , 0
       0     .12       0   310.6    .045       0   341.7     .12       0
  552.53     .06       0   583.9    .016       0
Bank Sta=310.6,341.7
XS Rating Curve= 0 ,0
Exp/Cntr=0.3,0.1

Type RM Length L Ch R = 1 ,23191.5 ,426.9,441.9,456.6
XS GIS Cut Line= 4
     2330424.557      355405.479       2330701.9      355430.219
        2330927.      355254.232     2331032.629      355234.906
#Sta/Elev= 30
       0  928.93    15.9  924.52   143.2   878.8   206.8  852.99   218.8  848.85
   234.7  844.86   278.4  836.14   294.3   834.7     338  832.87   417.3  834.64
   425.3  833.89   429.2  832.42   433.2  831.22   444.9  829.78     461   831.3
     465  832.65   468.9  833.95   484.8   833.8   504.6  835.04   552.3  835.36
   572.1  836.56  587.83 838.326     604  840.85  620.89842.0517   623.8  842.43
   627.8  844.46   639.7  854.22   647.7  858.95   659.6  864.12   671.6  867.95
#Mann= 5 ,-1 , 0
       0     .12       0   429.2    .045       0     465     .12       0
  587.83    .016       0  620.89     .12       0
#XS Ineff= 2 , 0
                          471.72             835
Permanent Ineff=
       F       F
Bank Sta=429.2,465
XS Rating Curve= 0 ,0
Exp/Cntr=0.3,0.1

Type RM Length L Ch R = 1 ,22749.6 ,341.5,340.2,338.4
XS GIS Cut Line= 4
     2330497.473      355763.552     2330769.881      355729.328
     2331049.791       355727.76     2331128.984      355788.292
#Sta/Elev= 30
       0  891.15    59.7  869.79    79.6  864.34    91.5   862.2   107.4  857.68
   123.4  854.72   163.1  845.66     195  840.16   258.6  834.66   322.5  831.92
   338.5  832.37   362.5  831.68   390.5  827.16   402.5  827.87   426.5  827.49
   442.5  828.36   470.5  828.22   482.5  825.72   490.5  825.52   494.5  825.84
   502.5  828.04   514.5  828.56  519.23829.5528   534.5  835.93   554.5  841.41
   582.4  854.72   598.3  861.18   614.3  866.22   646.2   878.3   654.1   879.6
#Mann= 4 ,-1 , 0
       0     .12       0   470.5    .045       0   502.5    .016       0
  519.23     .12       0
Bank Sta=470.5,502.5
XS Rating Curve= 0 ,0
Exp/Cntr=0.3,0.1

Type RM Length L Ch R = 1 ,22409.5 ,378.4,376.1,373.5
XS GIS Cut Line= 3
     2330584.713      356065.635     2331065.188      356027.959
     2331160.234      355977.094
#Sta/Elev= 30
       0  880.51       8  878.12    27.9  870.88    55.8  861.54   115.5  839.24
   143.4  833.13   183.2  828.95   215.1  827.56   250.9   827.1   286.8   827.5
   302.7   826.5   314.7  824.78   330.6  825.21   342.5  824.95   374.4     826
   396.5 823.647   414.2  821.34   418.2  821.66   426.5824.4615  434.68826.5922
   442.1  827.94     462  828.62     466  830.91     470  834.55  475.25837.3738
   485.9   842.7   493.9  845.68   505.9   851.2   557.8  869.67   589.8  876.19
#Mann= 5 ,-1 , 0
       0     .12       0   396.5    .045       0   426.5     .12       0
  434.68    .016       0  475.25     .12       0
Bank Sta=396.5,426.5
XS Rating Curve= 0 ,0
Exp/Cntr=0.3,0.1

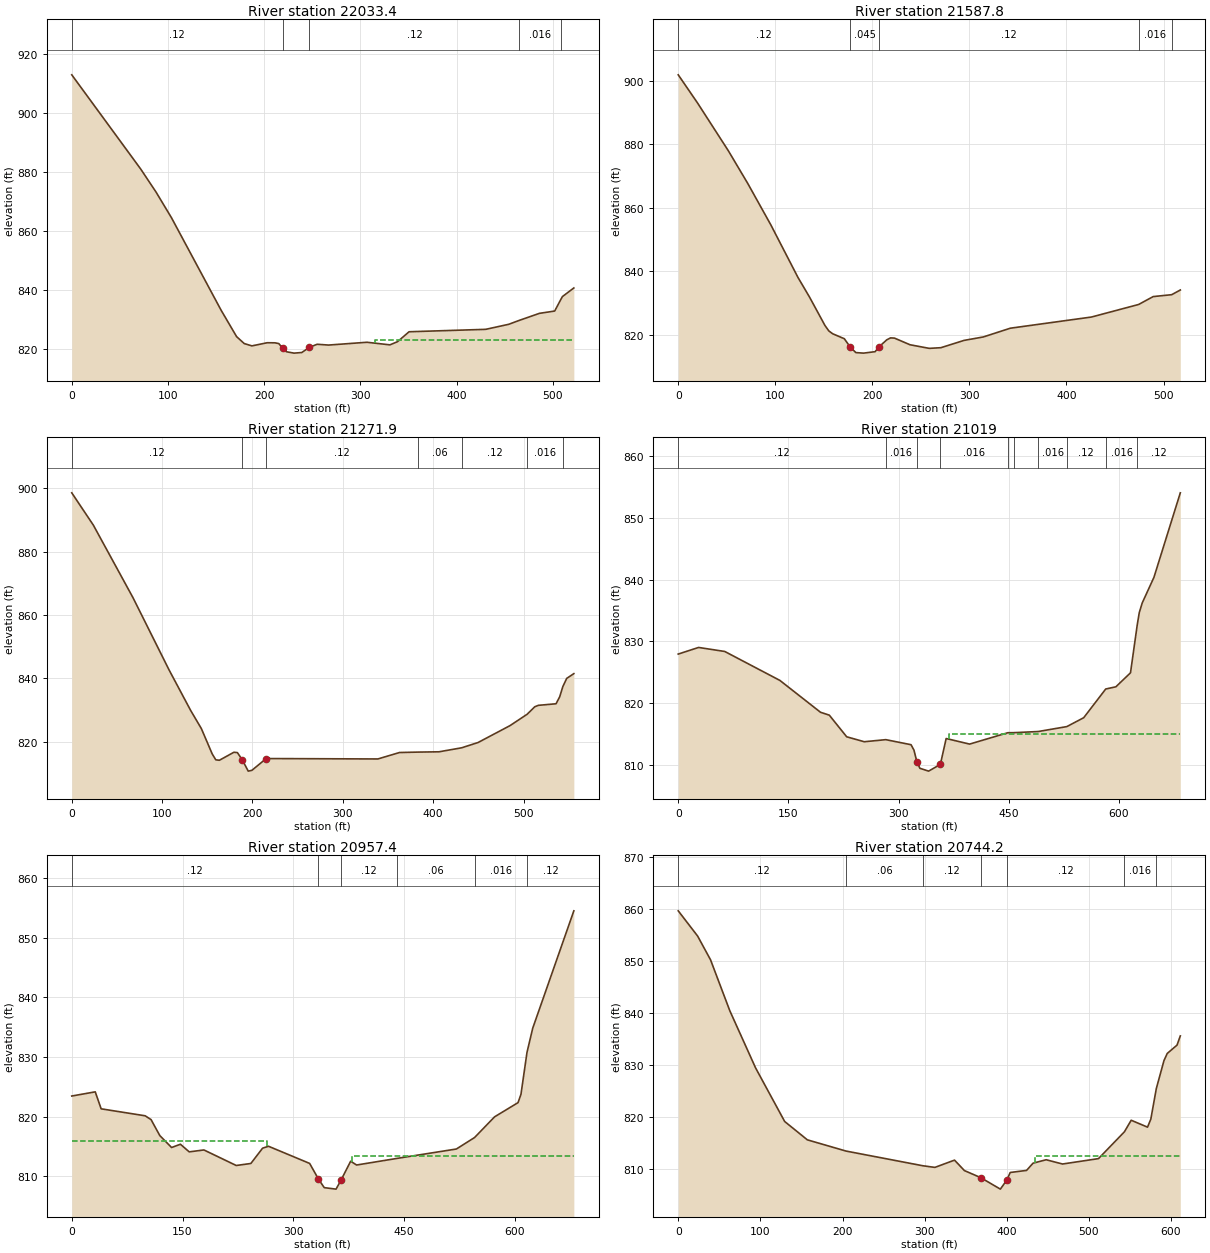
Type RM Length L Ch R = 1 ,22033.4 ,446.3,445.5,444.8
XS GIS Cut Line= 2
     2330673.254      356436.729     2331183.671      356328.656
#Sta/Elev= 30
       0     913    71.7  880.96    87.6  873.15   103.6  864.45   155.3  832.96
   171.3  824.05   179.2   821.7   187.2  820.91   203.1  821.98   211.1  821.95
   215.1   821.7     219  820.19     223  818.92     231  818.45     239  818.66
   246.9   820.4   254.9  821.46   266.8  821.19   306.7  822.14   330.6  821.26
   338.5  822.34   350.5  825.71   430.1  826.53     454  828.24  465.14829.5926
   485.9  831.96   501.8  832.75  507.88 836.498   509.8  837.65   521.7  840.59
#Mann= 5 ,-1 , 0
       0     .12       0     219    .045       0   246.9     .12       0
  465.14    .016       0  507.88     .12       0
#XS Ineff= 2 , 0
                          315.17          822.91
Permanent Ineff=
       F       F
Bank Sta=219,246.9
XS Rating Curve= 0 ,0
Exp/Cntr=0.3,0.1

Type RM Length L Ch R = 1 ,21587.8 ,313.9,316,318
XS GIS Cut Line= 2
     2330782.629       356849.49     2331285.234      356727.094
#Sta/Elev= 30
       0  901.83    19.9  892.96    51.7  877.88    71.6  867.64    95.5  854.52
   123.4     838   135.3  831.82   151.2  822.87   155.2  821.16   159.2  820.27
   171.1  818.72  177.18  816.11     183  814.35     191  814.18   202.9  814.64
   206.9  816.17   214.9  818.38   218.8  818.98   222.8  818.91   238.8  816.82
   258.6  815.68   270.6  815.89   294.5  818.19   314.4  819.28   342.2  822.03
   425.8  825.55  474.34829.5008   489.4  831.99  508.41832.5842   517.3  834.06
#Mann= 5 ,-1 , 0
       0     .12       0  177.18    .045       0   206.9     .12       0
  474.34    .016       0  508.41     .12       0
Bank Sta=177.18,206.9
XS Rating Curve= 0 ,0
Exp/Cntr=0.3,0.1

Type RM Length L Ch R = 1 ,21271.9 ,260.4,252.9,245.3
XS GIS Cut Line= 3
     2330855.546      357135.948     2331253.116      357072.774
     2331392.004      357008.344
#Sta/Elev= 30
       0  898.55    23.9  888.35    67.8  865.44   107.6  842.71   131.5  829.92
   143.5  824.11   155.4  816.17   159.4  814.29   163.4  814.15   179.4  816.67
   183.3  816.57  188.63  814.32   195.3  810.72   199.3  810.96   215.2  814.69
   338.8  814.56   362.7  816.59  383.51816.7268   406.5  816.82  431.55818.0843
   449.7  819.75     485  825.07     504828.6685   512.5  831.04   516.4  831.48
     536  831.98     540  834.16  543.56837.4279   547.8  839.98   555.7  841.49
#Mann= 7 ,-1 , 0
       0     .12       0  188.63    .045       0   215.2     .12       0
  383.51     .06       0  431.55     .12       0     504    .016       0
  543.56     .12       0
Bank Sta=188.63,215.2
XS Rating Curve= 0 ,0
Exp/Cntr=0.3,0.1

Type RM Length L Ch R = 1 ,21019   ,62.2,61.6,61.6
XS GIS Cut Line= 3
     2330865.963       357393.76     2331096.866      357360.534
     2331488.609      357138.954
#Sta/Elev= 30
       0  827.95    27.7  829.02    63.3  828.37   138.4  823.69   193.7  818.54
   205.6  818.08   229.3  814.58   253.2  813.78  282.51814.1165   316.9   813.3
   320.9  812.41   324.9  810.51   328.9  809.49   340.8  809.03   356.8  810.12
   364.7   814.3   396.6   813.4  448.76815.2382  456.36815.2422  489.96  815.43
  528.92816.2275   551.9  817.66  581.86822.3018   595.7  822.66   615.6  824.92
  624.88832.7556   627.6  834.68   631.6  836.22   647.5  840.35   683.4  854.01
#Mann= 10 ,-1 , 0
       0     .12       0  282.51    .016       0   324.9    .045       0
   356.8    .016       0  448.76     .06       0  456.36     .12       0
  489.96    .016       0  528.92     .12       0  581.86    .016       0
  624.88     .12       0
#XS Ineff= 2 , 0
                          369.14             815
Permanent Ineff=
       F       F
Bank Sta=324.9,356.8
XS Rating Curve= 0 ,0
Exp/Cntr=0.3,0.1

Type RM Length L Ch R = 1 ,20957.4 ,206,213.1,219.4
XS GIS Cut Line= 3
     2330901.553      357469.909     2331128.116      357408.711
      2331515.79      357189.433
#Sta/Elev= 30
       0  823.44    31.8  824.14    39.8  821.29    99.4  820.12   107.4  819.48
   119.3  816.79   135.2  814.79   147.2  815.34   159.1  814.06     179  814.38
   222.8  811.77   242.6  812.11   258.5  814.68   266.5     815   322.2  812.12
   334.1   809.5     342  808.05     358   807.8   364.8  809.33   377.8  812.49
   385.8  811.85  441.06812.9712     521  814.54  545.63816.4667   572.7  819.94
   604.5  822.33   608.5  823.74  616.63830.7628   624.4  834.83   680.1  854.55
#Mann= 6 ,-1 , 0
       0     .12       0   334.1    .045       0   364.8     .12       0
  441.06     .06       0  545.63    .016       0  616.63     .12       0
#XS Ineff= 2 , 0
           264.4  815.81  379.26          813.38
Permanent Ineff=
       F       F
Bank Sta=334.1,364.8
XS Rating Curve= 0 ,0
Exp/Cntr=0.3,0.1

Type RM Length L Ch R = 1 ,20744.2 ,331.7,334.2,336.7
XS GIS Cut Line= 3
     2331037.838       357643.76     2331155.459       357551.94
     2331604.244      357441.937
#Sta/Elev= 30
       0  859.59    23.6  854.74    39.3  850.18    62.8  840.37    94.2  829.37
   129.6  819.07   157.2  815.54  204.26813.3833  297.74810.5573   312.5  810.24
   336.4  811.64   348.4  809.63   368.3  808.27   392.2  806.06   400.2  807.83
   404.2  809.26   424.1  809.66     432  811.05     448  811.71   467.9  810.89
   511.7  811.93  543.26817.0903   551.5  819.31   571.4  817.98   575.4  819.52
   582.1825.4122   591.4  830.78   595.4  832.16   607.3  833.76   611.3  835.53
#Mann= 7 ,-1 , 0
       0     .12       0  204.26     .06       0  297.74     .12       0
   368.3    .045       0   400.2     .12       0  543.26    .016       0
   582.1     .12       0
#XS Ineff= 2 , 0
                          434.16          812.36
Permanent Ineff=
       F       F
Bank Sta=368.3,400.2
XS Rating Curve= 0 ,0
Exp/Cntr=0.3,0.1