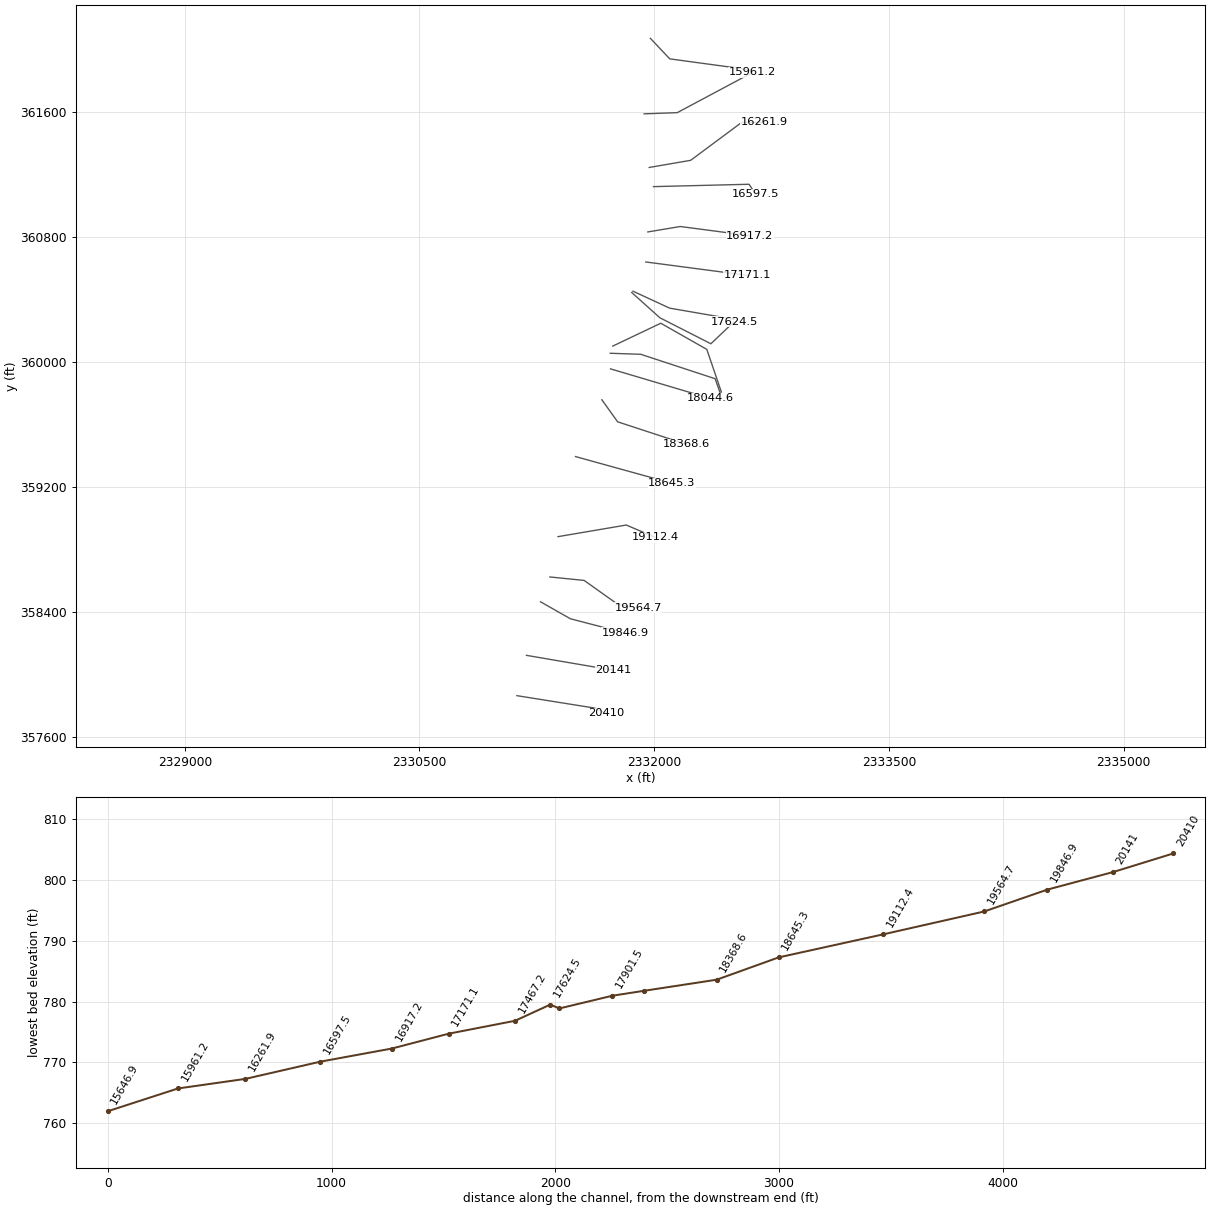
HEC-RAS study SFKSLPYCRK.prj: SFKSLPYCRK

--- SFKSLPYCRK.g01 (geometry) --- (continued)

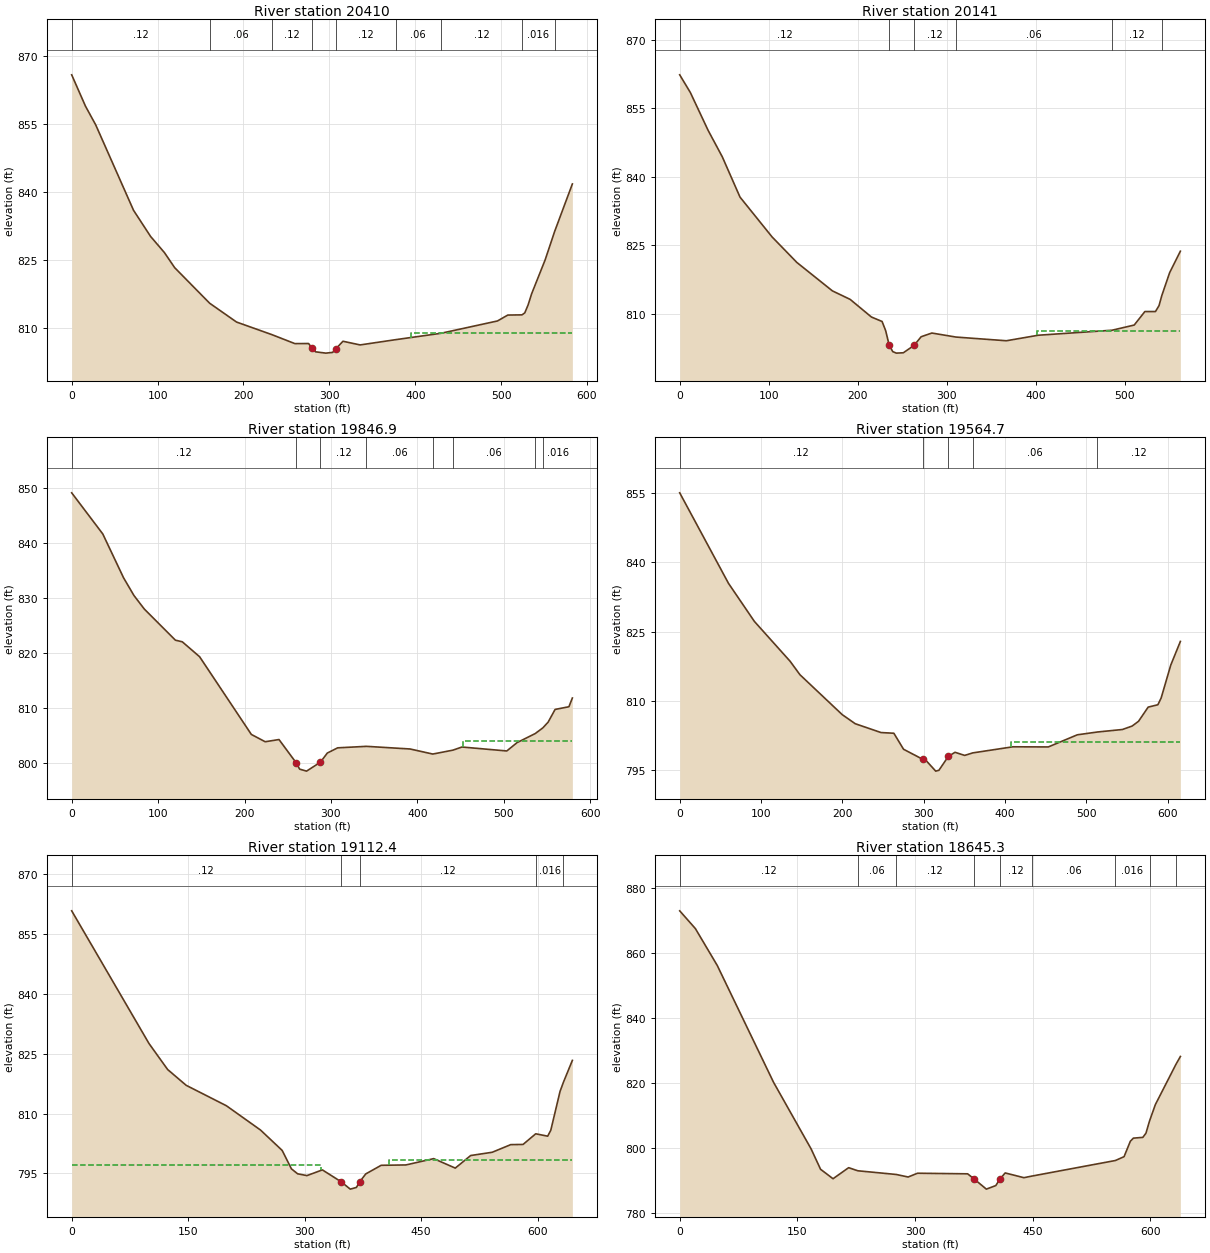
Type RM Length L Ch R = 1 ,20410   ,269.1,269,268.8
XS GIS Cut Line= 3
     2331122.473      357865.115     2331619.869      357785.687
     2331691.484      357751.833
#Sta/Elev= 30
       0   865.8      16   858.9      28  854.74      72   835.9    91.9  830.12
   107.9  826.58   119.9  823.24  160.64815.3898   191.9  811.24  233.09808.4597
   259.8  806.48   275.8   806.5   279.8  805.49   283.8  804.67   295.8  804.38
   303.8  804.54   307.8  805.38   315.8     807   335.8  806.19  377.14807.3502
  429.69808.7495   495.7  811.48   507.7  812.78  524.27812.8259   527.5  813.27
   531.4  815.03   535.4  817.44   551.2  824.96  562.22831.2087   582.9  841.72
#Mann= 9 ,-1 , 0
       0     .12       0  160.64     .06       0  233.09     .12       0
   279.8    .045       0   307.8     .12       0  377.14     .06       0
  429.69     .12       0  524.27    .016       0  562.22     .12       0
#XS Ineff= 2 , 0
                          395.05          808.87
Permanent Ineff=
       F       F
Bank Sta=279.8,307.8
XS Rating Curve= 0 ,0
Exp/Cntr=0.3,0.1

Type RM Length L Ch R = 1 ,20141   ,296.6,294.1,291.7
XS GIS Cut Line= 2
     2331183.671      358122.927     2331738.359      358027.875
#Sta/Elev= 30
       0  862.28      12  858.39    31.9  850.13    47.9  844.31    67.8  835.49
   103.8  826.78   131.7  821.18   171.6  814.96   191.6  813.09   215.5  809.23
   227.5  808.25   231.5  806.25   235.5  803.05   239.5  801.65   243.5  801.32
   251.4   801.4   263.4  803.01   271.4  804.91   283.4  805.72   310.6804.8383
   367.2  804.03   403.1  805.24  485.99806.3353   510.9  807.47   522.9  810.43
   534.8  810.43   538.8  811.73  541.96813.9499   550.8  818.98   562.8  823.64
#Mann= 6 ,-1 , 0
       0     .12       0   235.5    .045       0   263.4     .12       0
   310.6     .06       0  485.99     .12       0  541.96    .016       0
#XS Ineff= 2 , 0
                          401.86          806.27
Permanent Ineff=
       F       F
Bank Sta=235.5,263.4
XS Rating Curve= 0 ,0
Exp/Cntr=0.3,0.1

Type RM Length L Ch R = 1 ,19846.9 ,290.9,282.2,273.1
XS GIS Cut Line= 3
     2331273.515      358465.375     2331464.762      358356.792
     2331812.577      358266.156
#Sta/Elev= 30
       0  849.09      36   841.6      60  833.63      72  830.41      84  827.94
     120  822.27     128  821.97     148  819.26   207.9  805.11   223.9  803.78
   239.9  804.18   259.9  799.92   263.8  798.79   271.8  798.43   287.8  800.05
   295.8  801.72   307.8  802.67  341.13802.9414   391.6  802.46  417.87801.5389
  441.16802.2477   451.6  802.82   503.5   802.1   515.4  803.62  536.43805.2704
  545.24806.3046   551.4  807.36   559.4  809.66   575.4  810.15   579.4  811.74
#Mann= 8 ,-1 , 0
       0     .12       0   259.9    .045       0   287.8     .12       0
  341.13     .06       0  417.87     .12       0  441.16     .06       0
  536.43     .12       0  545.24    .016       0
#XS Ineff= 2 , 0
                          453.25          803.89
Permanent Ineff=
       F       F
Bank Sta=259.9,287.8
XS Rating Curve= 0 ,0
Exp/Cntr=0.3,0.1

Type RM Length L Ch R = 1 ,19564.7 ,429.7,452.2,472.7
XS GIS Cut Line= 4
     2331333.411      358624.229     2331552.161      358602.094
     2331768.307      358448.448     2331897.213      358426.312
#Sta/Elev= 30
       0     855      60  835.43    91.9  827.19   135.9  818.56   147.9  815.67
   199.9  807.04   215.9  805.08   247.6  803.17   263.4  803.02   275.3  799.56
     299  797.38     303  797.12   314.9  794.83   318.8  795.01   330.4798.0135
   338.6   798.9   350.5  798.23  360.43798.7718   409.8  800.09   453.4  800.06
     489  802.68  513.73803.2879   544.5  803.83   556.4  804.57   564.3   805.6
   576.2  808.67   588.1  809.18   592.1  810.62     604  817.77   615.8  822.87
#Mann= 5 ,-1 , 0
       0     .12       0     299    .045       0   330.4     .12       0
  360.43     .06       0  513.73     .12       0
#XS Ineff= 2 , 0
                          407.43          801.11
Permanent Ineff=
       F       F
Bank Sta=299,330.4
XS Rating Curve= 0 ,0
Exp/Cntr=0.3,0.1

Type RM Length L Ch R = 1 ,19112.4 ,477.5,467.1,456.7
XS GIS Cut Line= 3
     2331385.494      358882.042     2331821.692       358956.26
      2332007.89      358876.833
#Sta/Elev= 30
       0   860.8    99.6  827.54   123.6  821.03   147.5  817.07   199.3  811.95
   243.2  805.87   271.1  800.76     283  796.15     291   794.9     303  794.45
   322.9  795.88   346.8  792.94   358.8  791.06   366.7  791.48   371.2792.9387
   378.7  794.86   398.6  797.03   430.5  797.12   466.3   798.7   494.1  796.33
   513.9  799.48   541.7   800.3   565.5  802.21   581.4  802.26  597.69 804.925
   613.1  804.33   617.1  805.81     629  815.53  633.29817.8021   644.9  823.32
#Mann= 5 ,-1 , 0
       0     .12       0   346.8    .045       0   371.2     .12       0
  597.69    .016       0  633.29     .12       0
#XS Ineff= 2 , 0
          321.47  797.16  408.15          798.24
Permanent Ineff=
       F       F
Bank Sta=346.8,371.2
XS Rating Curve= 0 ,0
Exp/Cntr=0.3,0.1

Type RM Length L Ch R = 1 ,18645.3 ,277.8,276.8,275.7
XS GIS Cut Line= 2
     2331497.238      359394.014     2332112.473      359223.658
#Sta/Elev= 30
       0   872.9      20  867.43    47.9  856.08   119.7  820.12   167.6  799.62
   179.6  793.38   195.5  790.47   215.4  793.87  227.05792.9172  275.99791.7807
   291.3     791   303.2  792.16   367.1  791.98     375  790.47     391  787.27
     403  788.36  408.63  790.45     415  792.25   438.9  790.79  448.72791.2674
  555.59 796.077   566.6  797.26   574.6     802   578.5  802.96   590.5  803.19
   594.5  804.48  599.08  808.25   606.5  813.28  632.73825.6569   638.4  828.08
#Mann= 9 ,-1 , 0
       0     .12       0  227.05     .06       0  275.99     .12       0
     375    .045       0  408.63     .12       0  448.72     .06       0
  555.59    .016       0  599.08     .06       0  632.73     .12       0
Bank Sta=375,408.63
XS Rating Curve= 0 ,0
Exp/Cntr=0.3,0.1

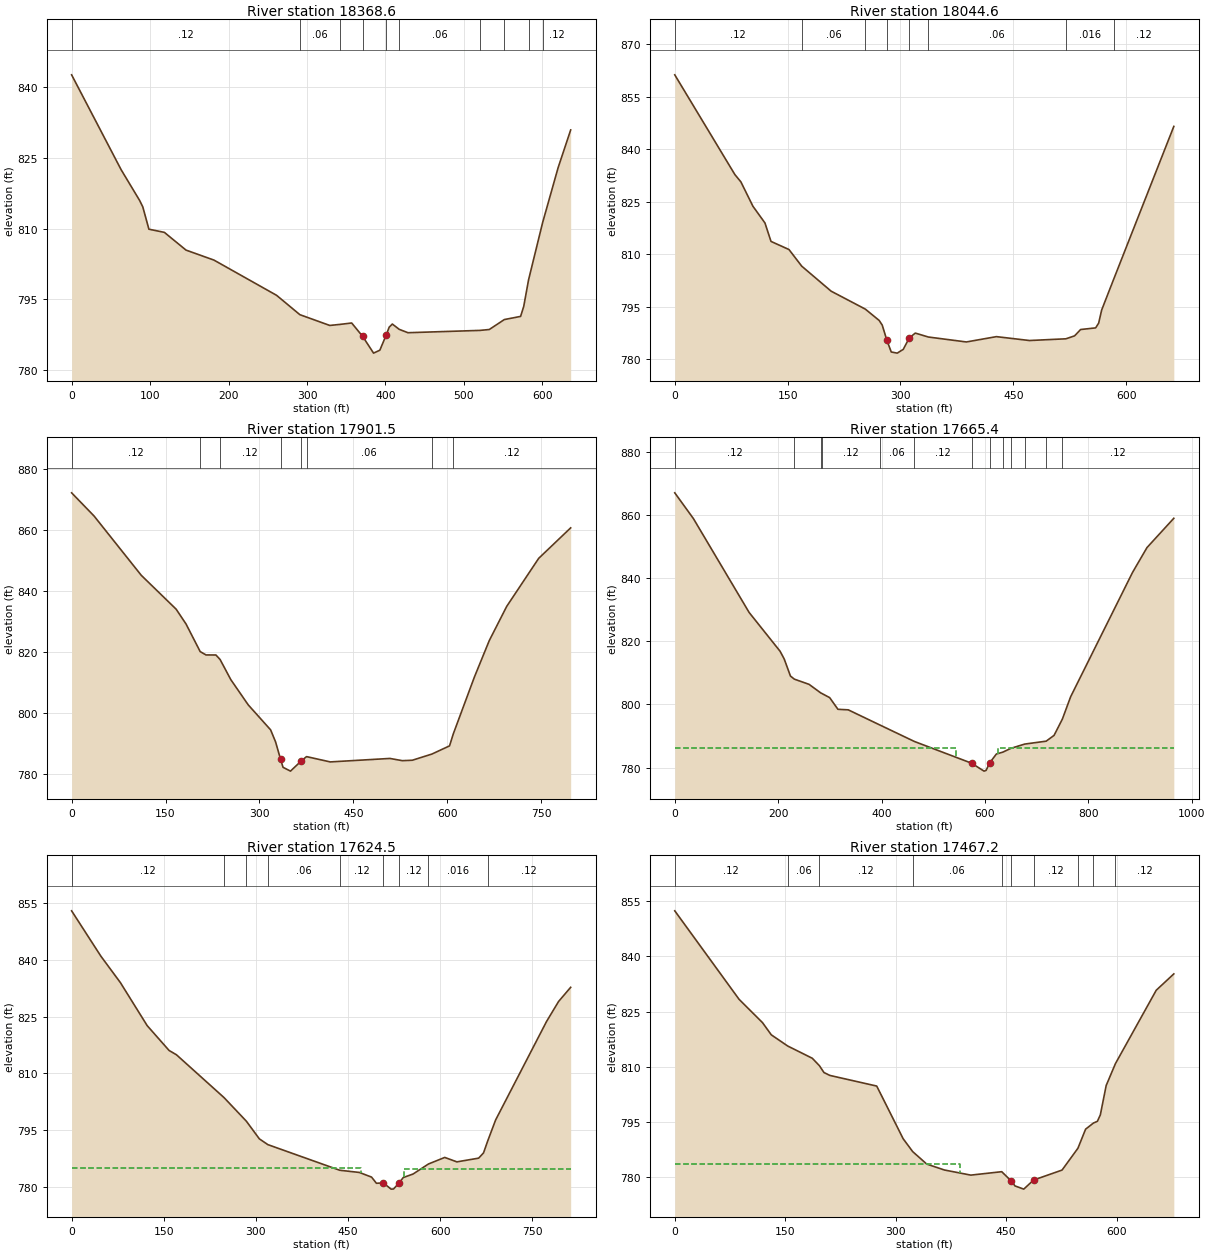
Type RM Length L Ch R = 1 ,18368.6 ,323.2,323.9,324.5
XS GIS Cut Line= 3
     2331665.424      359757.512     2331766.335      359616.453
     2332205.788      359472.139
#Sta/Elev= 30
       0  842.62    63.1   822.5    86.7  815.97    90.7  814.62    98.5  809.88
   118.2  809.21   145.8  805.45   181.4  803.33   261.2  795.86  290.89791.7547
     329  789.47  342.25789.6967   356.9  789.99   370.8 787.175   384.8   783.6
   392.8  784.22   400.8787.3937   404.7   789.1   408.7  789.77  417.55788.6423
   428.6  787.93  520.51788.4203   532.3  788.61  551.42 790.716   572.2  791.39
   576.2  793.53  582.32799.1304  600.25811.2823     620  822.93     636  830.93
#Mann= 10 ,-1 , 0
       0     .12       0  290.89     .06       0  342.25     .12       0
   370.8    .045       0   400.8     .12       0  417.55     .06       0
  520.51     .12       0  551.42    .016       0  582.32     .06       0
  600.25     .12       0
Bank Sta=370.8,400.8
XS Rating Curve= 0 ,0
Exp/Cntr=0.3,0.1

Type RM Length L Ch R = 1 ,18044.6 ,143.6,143.1,142.6
XS GIS Cut Line= 2
     2331720.762      359954.994     2332356.613      359766.192
#Sta/Elev= 30
       0  861.27    79.9  832.78    87.9  830.69   103.9  823.73   119.9  818.95
   127.9  813.69   151.8  811.37  168.75806.6212   207.8  799.48   253.3 794.348
   271.7  791.11   275.7   789.8  281.98  785.42   287.7  782.11   295.7  781.78
   303.7  782.86   311.7  786.13   319.7   787.5  337.14 786.377   387.6  784.97
   427.5  786.49   471.5  785.38  519.88 785.872   531.4  786.71   539.4  788.52
   559.4  788.99   563.4  790.35   567.4   794.1  583.18 802.788   663.3  846.54
#Mann= 8 ,-1 , 0
       0     .12       0  168.75     .06       0   253.3     .12       0
  281.98    .045       0   311.7     .12       0  337.14     .06       0
  519.88    .016       0  583.18     .12       0
Bank Sta=281.98,311.7
XS Rating Curve= 0 ,0
Exp/Cntr=0.3,0.1

Type RM Length L Ch R = 1 ,17901.5 ,240.5,236.1,231.6
XS GIS Cut Line= 4
     2331719.381       360054.67     2331914.053      360048.208
     2332389.314      359891.958     2332423.655        359795.8
#Sta/Elev= 30
       0  872.24    35.8  864.65   111.3  845.18     167  834.07   182.8  829.21
  205.37820.1692   214.6  819.07   230.5  819.05  237.14 817.587   254.3  810.97
   282.1   802.7   317.9  794.49   325.8  790.55   333.8  784.84   337.7  782.22
   349.6  780.96   366.8784.2945  375.26785.7209   413.2  783.98   508.4  785.12
   528.3  784.39   544.2  784.53   575.6 786.564   603.7  789.24  609.75793.2072
   643.4  811.82   667.3  823.83   695.1  835.02   746.1  850.75   797.2  860.75
#Mann= 8 ,-1 , 0
       0     .12       0  205.37     .06       0  237.14     .12       0
   333.8    .045       0   366.8     .12       0  375.26     .06       0
   575.6    .016       0  609.75     .12       0
Bank Sta=333.8,366.8
XS Rating Curve= 0 ,0
Exp/Cntr=0.3,0.1

Type RM Length L Ch R = 1 ,17665.4 ,40.3,41,41.6
XS GIS Cut Line= 4
      2331735.43      360100.705     2332042.091      360246.775
     2332336.145      360079.675     2332429.154      359807.502
#Sta/Elev= 30
       0  867.02      36  858.88   143.9  829.12   203.8  816.83   211.8  814.37
   223.8  808.99  231.39808.0021   259.8  806.36  282.32803.6569  284.53803.4711
   299.7  802.15   315.7  798.45   335.7  798.28  396.28793.5242  463.78788.2505
   574.4  781.37   598.3  778.87   602.3   779.1   609.4781.5118   622.2  784.29
  634.48784.8714  650.64786.1076  677.12787.4412  718.51788.3544   733.8  790.19
  749.89795.3485   765.8   802.4   885.6   841.8   913.6  849.68   965.5  858.96
#Mann= 13 ,-1 , 0
       0     .12       0  231.39    .016       0  282.32     .06       0
  284.53     .12       0  396.28     .06       0  463.78     .12       0
   574.4    .045       0   609.4    .016       0  634.48     .12       0
  650.64     .08       0  677.12    .016       0  718.51     .06       0
  749.89     .12       0
#XS Ineff= 2 , 0
          543.86  786.15  625.39          786.15
Permanent Ineff=
       F       F
Bank Sta=574.4,609.4
XS Rating Curve= 0 ,0
Exp/Cntr=0.3,0.1

Type RM Length L Ch R = 1 ,17624.5 ,150.3,157.3,164.8
XS GIS Cut Line= 4
     2331856.544      360443.173     2332036.666      360281.498
     2332362.187      360115.482     2332510.841      360256.541
#Sta/Elev= 30
       0  852.89    47.6  840.94    79.4  833.96     123  822.62   158.7  816.06
   170.6  814.94  248.09 803.641  284.52797.4035   305.6  792.76   319.4791.2397
  436.46784.4784   468.4   783.9   488.3  782.67   496.2  781.04   507.3781.1497
   520.1   779.5     524  779.53  533.41   781.2   539.9  782.56   555.8  783.48
  580.89786.1293   607.4  787.86   627.2  786.69   662.6  787.67   670.5  789.05
  677.57792.2974   690.2  797.73     773  823.67   792.7  828.98   812.4  832.72
#Mann= 9 ,-1 , 0
       0     .12       0  248.09     .06       0  284.52     .12       0
   319.4     .06       0  436.46     .12       0   507.3    .045       0
  533.41     .12       0  580.89    .016       0  677.57     .12       0
#XS Ineff= 2 , 0
          470.59  785.05   541.8           784.9
Permanent Ineff=
       F       F
Bank Sta=507.3,533.41
XS Rating Curve= 0 ,0
Exp/Cntr=0.3,0.1

Type RM Length L Ch R = 1 ,17467.2 ,295.4,296.1,296.1
XS GIS Cut Line= 3
      2331864.14      360451.854     2332098.515      360343.347
     2332511.926      360271.732
#Sta/Elev= 30
       0  852.34    87.4  828.32   119.2     822   131.1   818.7  153.38815.6658
   186.8  812.34  196.45810.3281   202.6  808.48   210.6  807.69   274.3   804.8
   310.2  790.51  323.14787.0185   342.2  783.64   366.2  782.03   402.1  780.64
  444.09781.5707   457.3 778.986   462.1  777.71     474  776.84   487.3779.3005
     526  782.01  547.54787.9244     558  793.11   568.6 794.762     574  795.24
     578  796.98   585.9  804.93  598.48810.8832   653.9  830.79   677.8  835.23
#Mann= 10 ,-1 , 0
       0     .12       0  153.38     .06       0  196.45     .12       0
  323.14     .06       0  444.09     .12       0   457.3    .045       0
   487.3     .12       0  547.54    .016       0   568.6     .06       0
  598.48     .12       0
#XS Ineff= 2 , 0
           387.2  783.65
Permanent Ineff=
       F       F
Bank Sta=457.3,487.3
XS Rating Curve= 0 ,0
Exp/Cntr=0.3,0.1

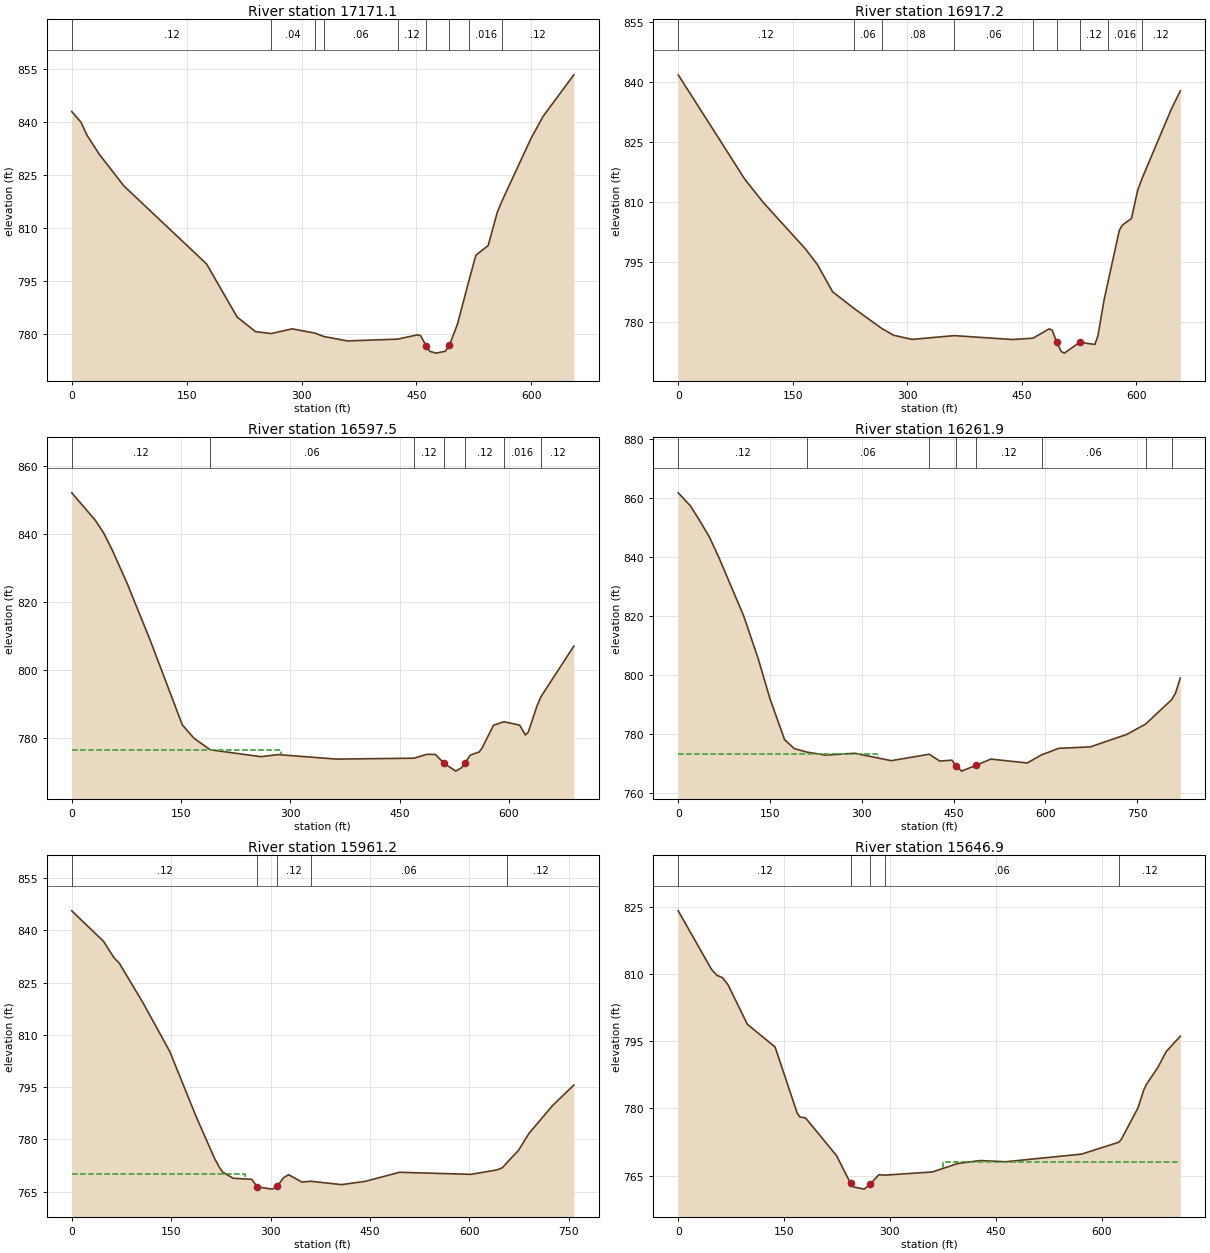
Type RM Length L Ch R = 1 ,17171.1 ,253.8,253.8,253.9
XS GIS Cut Line= 2
     2331946.457      360638.588     2332596.413      360552.868
#Sta/Elev= 30
       0     843      12  840.01      20  836.28      36  830.92      68     822
   175.9  799.96   215.9  784.94   239.8  780.81  260.46780.2534   287.8  781.58
  318.06780.3513  329.07779.4225   359.8  778.17  425.44 778.673   451.7   779.9
   455.7  779.62     463776.5973   467.7  775.22   475.7  774.72   487.7  775.25
     493776.8893   503.7  782.96  518.35     795   527.7  802.41   543.7  805.13
   555.6  814.52   562.4 818.022   599.6  835.38   615.6   841.7   655.6  853.39
#Mann= 9 ,-1 , 0
       0     .12       0  260.46     .04       0  318.06     .12       0
  329.07     .06       0  425.44     .12       0     463    .045       0
     493     .12       0  518.35    .016       0   562.4     .12       0
Bank Sta=463,493
XS Rating Curve= 0 ,0
Exp/Cntr=0.3,0.1

Type RM Length L Ch R = 1 ,16917.2 ,316.2,319.7,323.3
XS GIS Cut Line= 3
     2331959.478      360830.646     2332166.726      360865.368
     2332610.519      360806.774
#Sta/Elev= 30
       0  841.85    87.2  815.76     111  810.03   166.5  798.37   182.4   794.4
   202.2  787.63  230.61783.4146  267.09778.3864   282.1  776.76   306.1  775.71
  361.67776.6569     438  775.68  464.87 776.017   485.9  778.34   489.9  778.03
  496.03  774.94   501.9  772.66   505.9  772.28   525.9  774.98   545.9  774.45
   549.9  776.65   557.9  785.56  563.58790.5145   577.8  802.92   581.8  804.27
   593.8  805.94   601.8  812.89  607.42815.8166   645.8  833.18   657.8  837.83
#Mann= 9 ,-1 , 0
       0     .12       0  230.61     .06       0  267.09     .08       0
  361.67     .06       0  464.87     .12       0  496.03    .045       0
   525.9     .12       0  563.58    .016       0  607.42     .12       0
Bank Sta=496.03,525.9
XS Rating Curve= 0 ,0
Exp/Cntr=0.3,0.1

Type RM Length L Ch R = 1 ,16597.5 ,321,335.6,350.1
XS GIS Cut Line= 3
     2331995.285      361120.359     2332606.179       361135.55
     2332649.582      361070.446
#Sta/Elev= 30
       0  852.23      32  844.22    43.9  840.35    55.9  835.21    75.9  825.57
   107.8  808.66   151.8  783.75   167.8  779.82  190.15776.4069   259.6  774.39
   283.6  774.99   363.4  773.67  469.83773.9331   487.3  775.07   499.2  775.05
   511.2  772.42   527.2  770.12   535.2  771.13  539.97  772.56   547.2  774.87
   559.2  775.75   563.2  776.89   579.1  783.67  593.35784.6906     615  783.69
   622.8  780.79   626.7  781.62   638.5  789.23  644.16792.0724   689.3     807
#Mann= 7 ,-1 , 0
       0     .12       0  190.15     .06       0  469.83     .12       0
   511.2    .045       0  539.97     .12       0  593.35    .016       0
  644.16     .12       0
#XS Ineff= 2 , 0
          287.51  776.39
Permanent Ineff=
       F       F
Bank Sta=511.2,539.97
XS Rating Curve= 0 ,0
Exp/Cntr=0.3,0.1

Type RM Length L Ch R = 1 ,16261.9 ,304.7,300.7,296.3
XS GIS Cut Line= 4
     2331968.158      361242.972     2332232.915      361288.545
     2332560.827      361532.389     2332703.835        361531.6
#Sta/Elev= 30
       0  861.79    19.8  857.39    35.6  852.16    51.4   846.6    67.2  839.45
   106.7  820.12   130.4  805.62   150.1  791.75   173.8  777.95   189.6  774.94
  210.07773.7465     241  772.73   288.5  773.34     348  770.83  410.03773.0128
   427.4  770.69   447.2     771  453.81  769.11     463  767.28   486.9  769.27
   510.7  771.37   570.2  770.05  593.64772.8086   621.8  775.02   673.3  775.51
   732.9  779.75  763.45783.2381  805.99791.5116   812.4  793.74   820.3  798.88
#Mann= 8 ,-1 , 0
       0     .12       0  210.07     .06       0  410.03     .12       0
  453.81    .045       0   486.9     .12       0  593.64     .06       0
  763.45     .12       0  805.99    .016       0
#XS Ineff= 2 , 0
          326.11  772.97
Permanent Ineff=
       F       F
Bank Sta=453.81,486.9
XS Rating Curve= 0 ,0
Exp/Cntr=0.3,0.1

Type RM Length L Ch R = 1 ,15961.2 ,328.3,314.2,300.1
XS GIS Cut Line= 3
     2331935.606      361585.854     2332147.195      361593.449
     2332628.966      361850.611
#Sta/Elev= 30
       0  845.65    47.9   836.9    63.9  832.13    71.9  830.57   107.9   819.1
   147.8   805.3   187.8  786.51   215.7  774.44   223.7   771.7   227.7   770.6
   243.6  768.83   271.5  768.53   280.2766.3465   302.7  765.71   310.2 766.557
   319.4  768.93   327.3  769.86   347.3  767.74  360.87767.9684     407     767
   442.9  767.94   494.7  770.55   602.4  769.95   642.2  771.25   650.2  771.89
  657.48773.4764   674.1   776.8   690.1  781.72   725.9  789.76   757.8   795.6
#Mann= 5 ,-1 , 0
       0     .12       0   280.2    .045       0   310.2     .12       0
  360.87     .06       0  657.48     .12       0
#XS Ineff= 2 , 0
          260.89  769.97
Permanent Ineff=
       F       F
Bank Sta=280.2,310.2
XS Rating Curve= 0 ,0
Exp/Cntr=0.3,0.1

Type RM Length L Ch R = 1 ,15646.9 ,285.7,284.9,284
XS GIS Cut Line= 3
     2331975.754       362068.71     2332099.452      361937.416
      2332625.71      361865.802
#Sta/Elev= 30
       0  824.08    47.1  811.02    54.9  809.68    62.7  809.16    70.6  807.57
      98  798.75   137.2   793.7   168.6  778.93   172.5  778.05   180.4  777.86
   224.3  769.45   244.3  763.22   248.3  762.46   263.5  761.96   272.2  763.07
   284.2  765.17  292.82  765.08   360.1  765.79     396  767.67     428  768.34
   463.9  768.07   571.7  769.78  624.36772.4292   627.6  772.98   651.6  780.12
   659.6  784.04   663.6  785.38   679.6   789.1   691.5  792.66   711.5  796.09
#Mann= 5 ,-1 , 0
       0     .12       0   244.3    .045       0   272.2     .12       0
  292.82     .06       0  624.36     .12       0
#XS Ineff= 2 , 0
                          375.64          768.04
Permanent Ineff=
       F       F
Bank Sta=244.3,272.2
XS Rating Curve= 0 ,0
Exp/Cntr=0.3,0.1