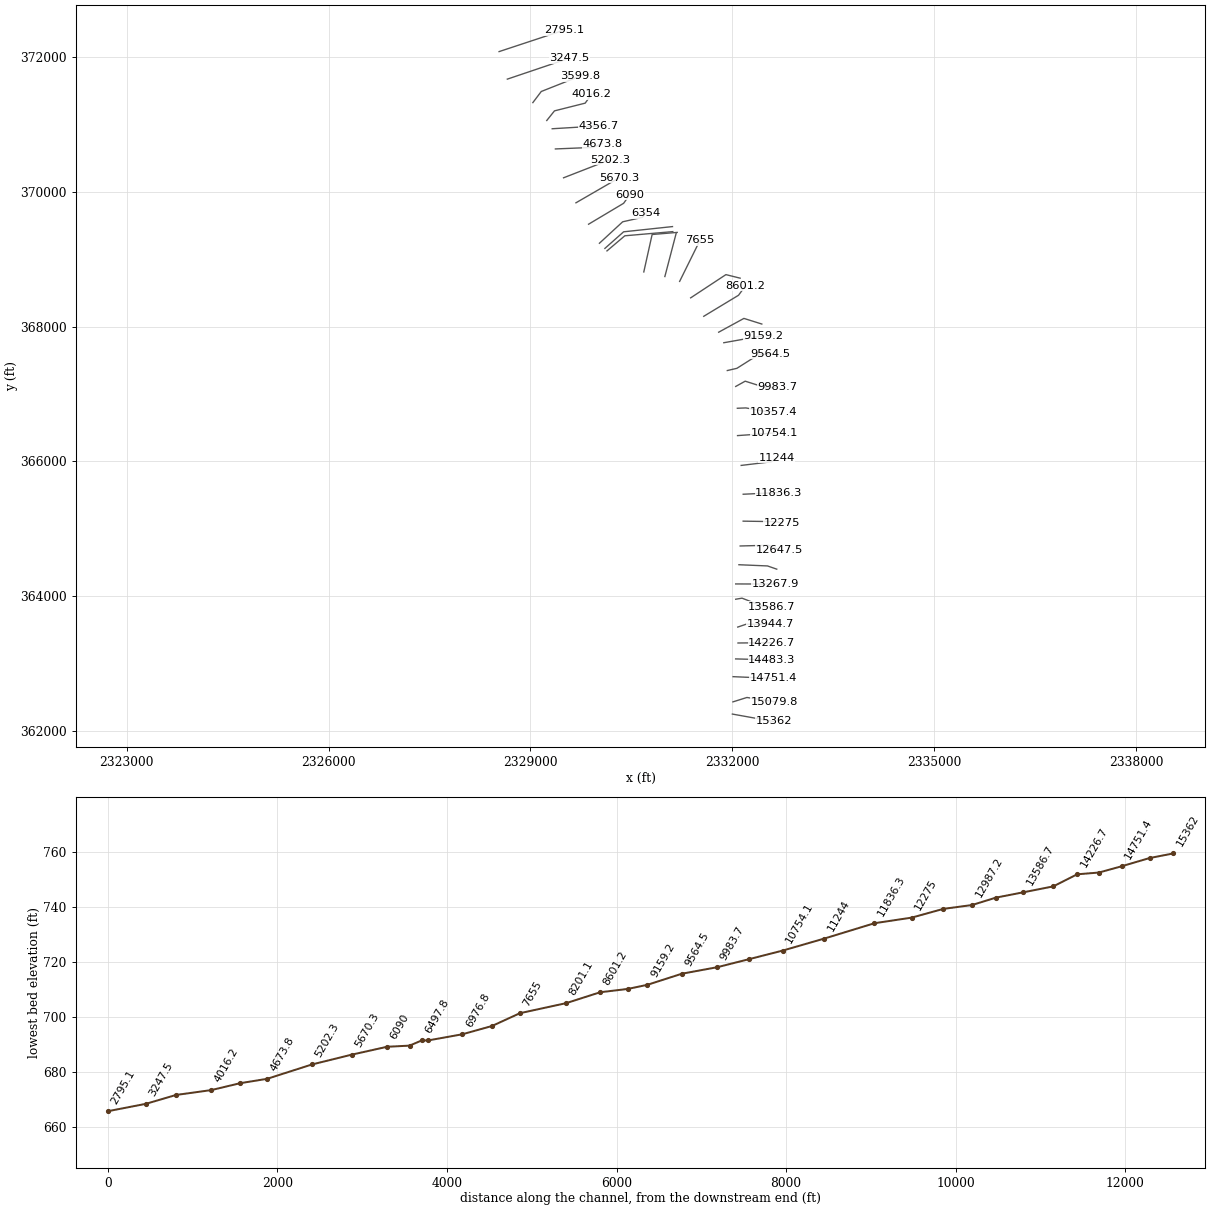
HEC-RAS study SFKSLPYCRK.prj: SFKSLPYCRK

--- SFKSLPYCRK.g01 (geometry) --- (continued)

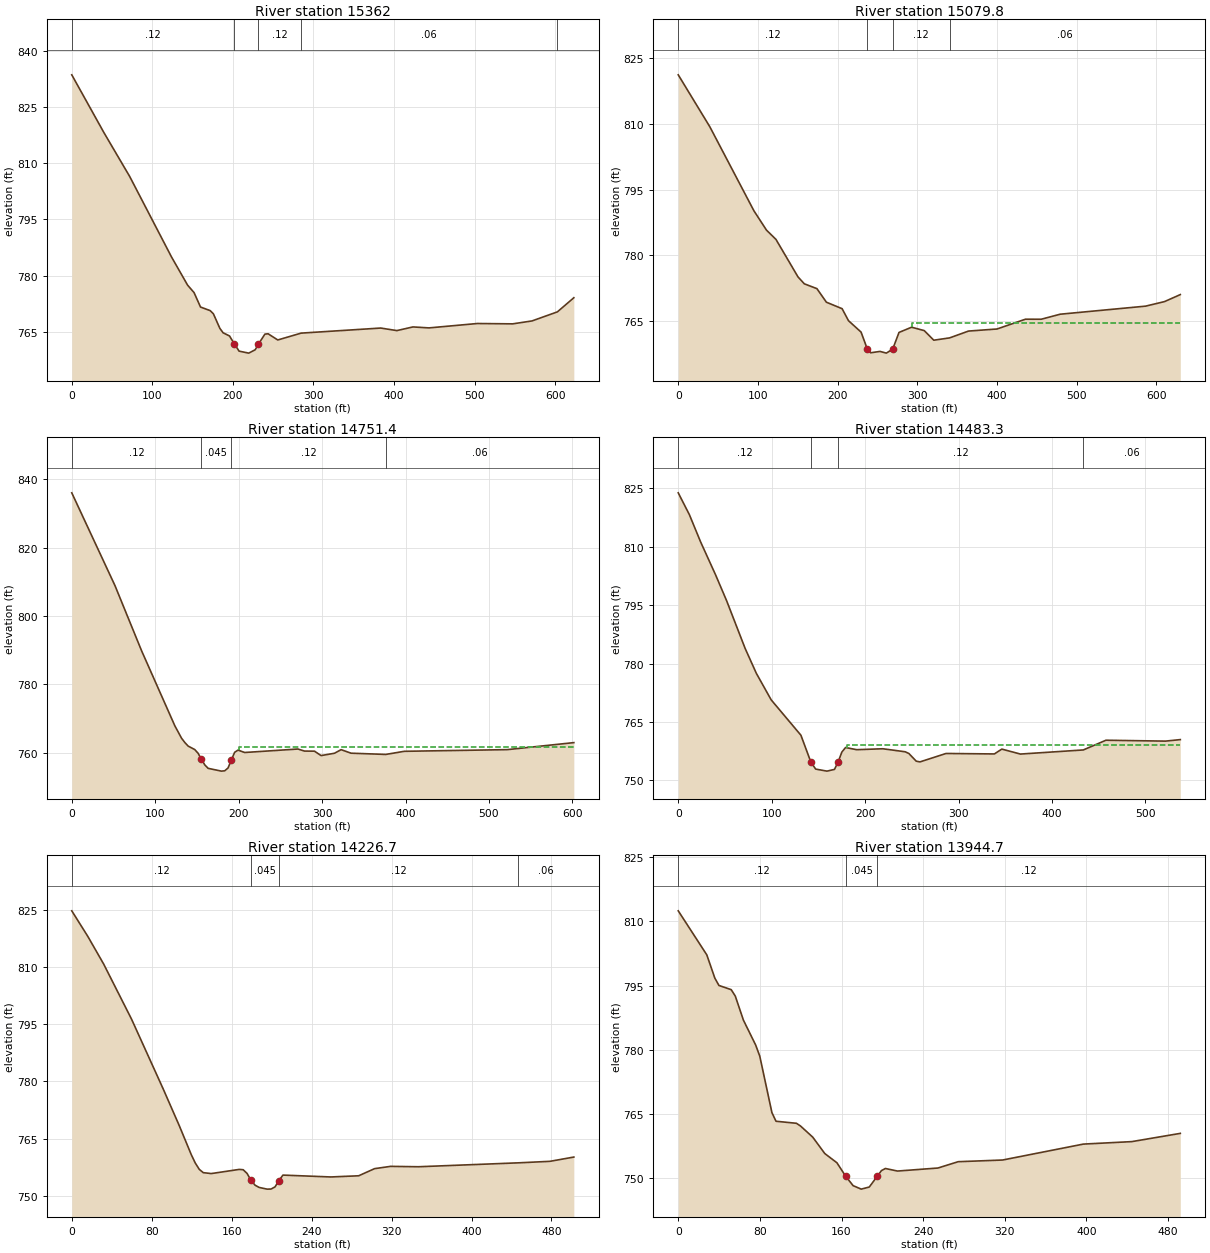
Type RM Length L Ch R = 1 ,15362   ,281.6,282.2,282.8
XS GIS Cut Line= 2
      2331998.54      362245.576     2332611.927      362135.295
#Sta/Elev= 30
       0  833.58      40  818.13    71.9  806.46   123.8  784.99   143.8  777.46
   151.8  775.48   159.8  771.63   171.8  770.67   175.8  769.82   183.8  765.95
   187.8  764.76   195.8  763.91  201.74  761.82   207.7  759.86   219.7  759.33
   227.7  760.23   231.7  761.72   239.7   764.4   243.7  764.49   255.7  762.84
   284.7764.6667   383.5  766.02   403.5  765.34   423.5  766.32   443.4  766.06
   503.4  767.23   547.3  767.14   571.3  767.92  602.76770.3349   623.2  774.11
#Mann= 5 ,-1 , 0
       0     .12       0  201.74    .045       0   231.7     .12       0
   284.7     .06       0  602.76     .12       0
Bank Sta=201.74,231.7
XS Rating Curve= 0 ,0
Exp/Cntr=0.3,0.1

Type RM Length L Ch R = 1 ,15079.8 ,325.9,328.4,330.9
XS GIS Cut Line= 3
     2332007.221      362426.783     2332214.722         362492.
     2332622.455      362430.038
#Sta/Elev= 30
       0  821.21    39.6  809.36    94.9  790.17   110.7  785.74   122.6  783.62
   150.3  775.04   158.2  773.47     174  772.37   185.9  769.27   205.6  767.79
   213.6  765.05   229.4  762.44   237.3  758.53   241.3  757.72   253.2  758.03
   261.1  757.64   269.1  758.57     277  762.37   292.8  763.56   308.7  762.78
   320.6  760.59  340.52761.1232   364.2  762.68   399.9  763.15   435.6  765.39
   455.4  765.38   479.2  766.53   586.3  768.37   610.1  769.41   629.9  771.01
#Mann= 4 ,-1 , 0
       0     .12       0   237.3    .045       0   269.1     .12       0
  340.52     .06       0
#XS Ineff= 2 , 0
                          293.29          764.59
Permanent Ineff=
       F       F
Bank Sta=237.3,269.1
XS Rating Curve= 0 ,0
Exp/Cntr=0.3,0.1

Type RM Length L Ch R = 1 ,14751.4 ,267.7,268.1,268.5
XS GIS Cut Line= 2
     2332009.391      362801.132     2332610.519       362775.09
#Sta/Elev= 30
       0  835.98    51.8  808.86    83.7  789.81   123.5  767.92   131.5   764.3
   135.5  763.02   139.5  761.97   147.4  760.96   151.4  759.88   155.4  758.11
   159.4  756.49   163.4  755.48   179.3  754.66   183.3  754.76   187.3  755.58
   191.3  757.95   195.2  760.15   199.2  760.81   207.2   760.1     271  761.12
   278.9  760.52   290.9  760.49   298.8   759.2   314.8  759.88   322.8  760.93
   334.7   759.9  376.26759.5368   398.5  760.45     522  760.94   601.7  762.99
#Mann= 4 ,-1 , 0
       0     .12       0   155.4    .045       0   191.3     .12       0
  376.26     .06       0
#XS Ineff= 2 , 0
                           200.1          761.62
Permanent Ineff=
       F       F
Bank Sta=155.4,191.3
XS Rating Curve= 0 ,0
Exp/Cntr=0.3,0.1

Type RM Length L Ch R = 1 ,14483.3 ,255.7,256.6,257.4
XS GIS Cut Line= 2
     2332047.368      363064.804     2332584.478      363050.698
#Sta/Elev= 30
       0   823.8    11.9  818.21    23.9  811.23    39.8  802.84    51.7  796.16
    71.6  783.87    83.6  777.47    99.5  770.66   131.3  761.59  141.94   754.7
   147.1   752.9   159.2  752.38   167.2  752.82   171.1  754.74   175.1  757.27
   179.1  758.44     191  757.88   218.9  758.12   242.8  757.35   246.8  756.91
   254.7  754.93   258.7  754.75   286.6  756.91   338.3  756.79   346.3  758.03
   366.2  756.76  433.49757.8137   457.7  760.31   521.4  760.08   537.3  760.47
#Mann= 4 ,-1 , 0
       0     .12       0  141.94    .045       0   171.1     .12       0
  433.49     .06       0
#XS Ineff= 2 , 0
                          180.19          759.19
Permanent Ineff=
       F       F
Bank Sta=141.94,171.1
XS Rating Curve= 0 ,0
Exp/Cntr=0.3,0.1

Type RM Length L Ch R = 1 ,14226.7 ,282.2,282,281.8
XS GIS Cut Line= 2
     2332082.091      363301.349     2332584.478      363305.689
#Sta/Elev= 30
       0  824.73      16  818.05    31.9  810.78    59.8  796.33    91.7  777.89
   107.7  768.31   119.6  760.77   123.6  758.58   127.6  756.92   131.6  756.06
   139.6  755.82   167.5  756.91   171.5  756.83   175.4  755.86   179.4  754.03
   183.4  752.78   187.4  752.19   195.4  751.74   199.4  751.76   203.4  752.33
   207.3  753.99   211.3  755.42   259.2  754.93   287.1  755.24     303  757.11
     319  757.71   346.9  757.61  446.92758.6348   478.5  759.03   502.4  760.15
#Mann= 4 ,-1 , 0
       0     .12       0   179.4    .045       0   207.3     .12       0
  446.92     .06       0
Bank Sta=179.4,207.3
XS Rating Curve= 0 ,0
Exp/Cntr=0.3,0.1

Type RM Length L Ch R = 1 ,13944.7 ,366.3,357.9,349.5
XS GIS Cut Line= 3
     2332078.835      363537.894     2332203.618      363580.211
     2332563.861      363580.211
#Sta/Elev= 30
       0  812.49      28  802.18    35.9  796.72    39.9  795.02    51.9  794.04
    55.9  792.54    63.9  786.89    75.9  781.07    79.9  778.48    91.8  765.26
    95.8  763.24   115.8  762.76   119.8  762.13   131.8  759.52   143.6  755.68
   155.5  753.52  164.25  750.31   171.4  748.16   179.3  747.35   187.2  747.84
   195.1  750.38   199.1  751.68     203  752.18   214.9  751.58   254.5  752.29
   274.3  753.77   317.8  754.16     397  757.89   444.5  758.47     492   760.4
#Mann= 3 ,-1 , 0
       0     .12       0  164.25    .045       0   195.1     .12       0
Bank Sta=164.25,195.1
XS Rating Curve= 0 ,0
Exp/Cntr=0.3,0.1

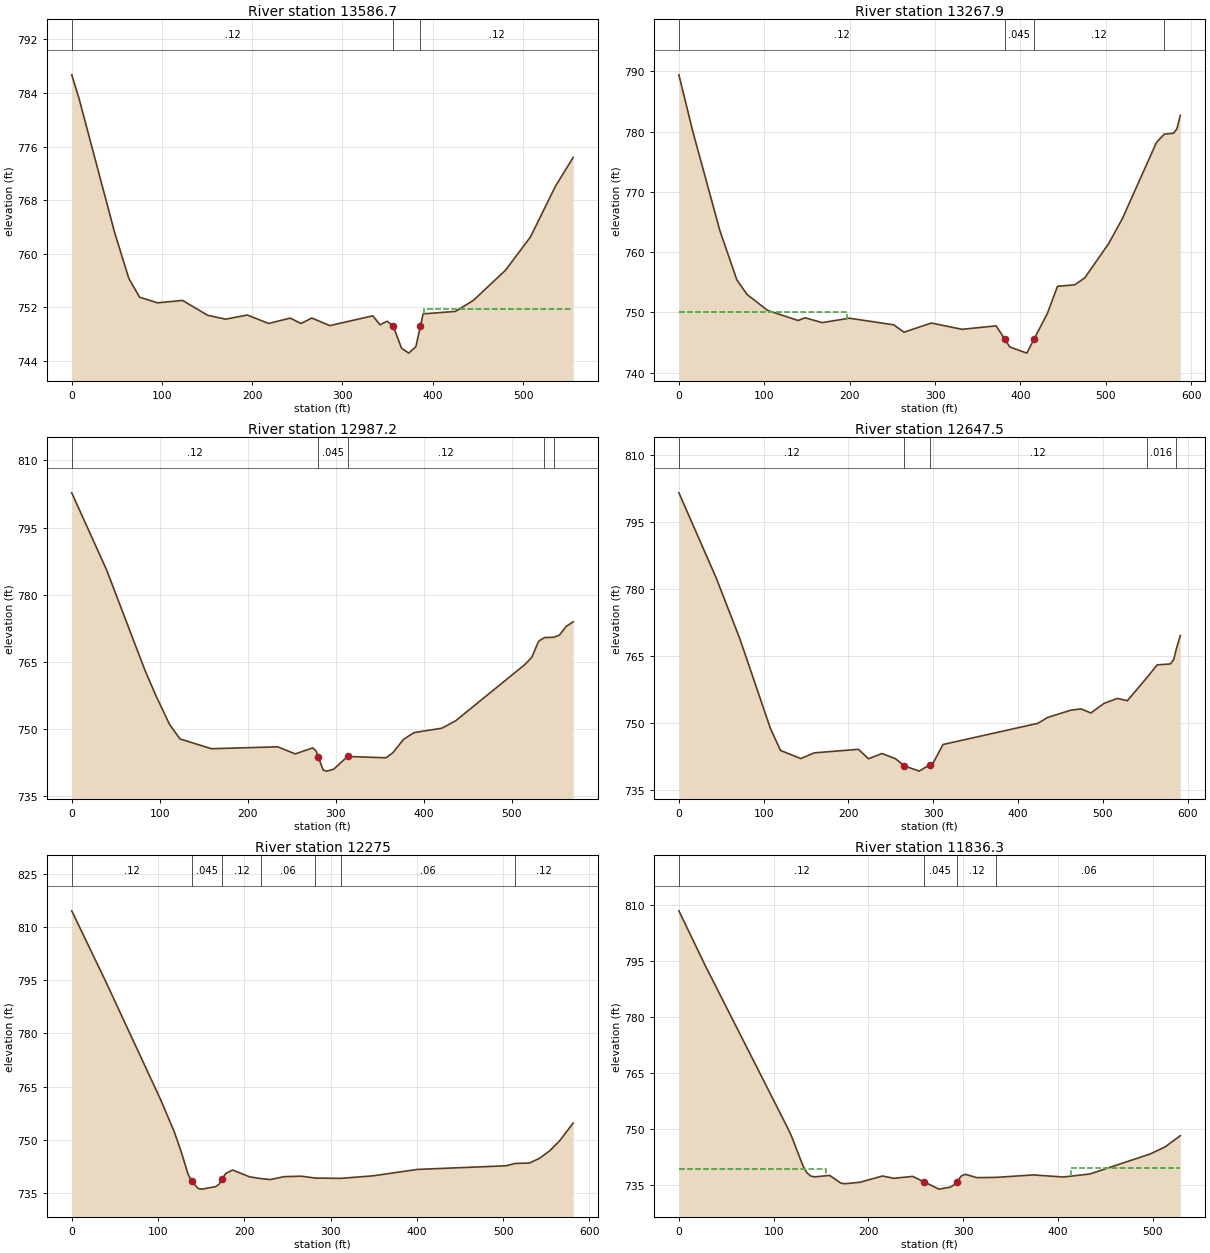
Type RM Length L Ch R = 1 ,13586.7 ,310.6,318.9,327.1
XS GIS Cut Line= 4
     2332048.453      363951.305     2332142.057      363967.237
     2332468.375      363840.628     2332579.052      363839.543
#Sta/Elev= 30
       0  786.72     7.9  783.28    47.5  763.19    63.3  756.31    75.2  753.52
      95  752.68   122.8  753.04   150.6  750.82   170.5  750.24   194.4  750.86
   218.2   749.6   242.1   750.4     254  749.59     266  750.41   285.9  749.28
   333.6  750.74   341.6   749.4   349.5  749.93   356.3 749.176   365.4  745.91
   373.4  745.17   381.3  746.14   386.3749.1475   389.3  751.03   425.1   751.4
     445  753.04   480.6  757.55   508.2   762.5   535.9  770.07   555.6   774.4
#Mann= 3 ,-1 , 0
       0     .12       0   356.3    .045       0   386.3     .12       0
#XS Ineff= 2 , 0
                          390.09          751.82
Permanent Ineff=
       F       F
Bank Sta=356.3,386.3
XS Rating Curve= 0 ,0
Exp/Cntr=0.3,0.1

Type RM Length L Ch R = 1 ,13267.9 ,281.5,280.7,279.9
XS GIS Cut Line= 2
     2332048.274      364178.392     2332635.656      364176.693
#Sta/Elev= 30
       0   789.4      16  780.17      48  763.57    67.9   755.4    79.9  752.98
   103.9  750.34   139.8  748.67   147.8  749.12   167.8  748.32   199.8  749.05
   251.7  747.95   263.7  746.73   295.7  748.25   331.6  747.21   371.6  747.78
  381.61  745.61   387.6  744.28   407.6  743.26   415.9745.5585   431.6  749.82
   443.5  754.34   463.5  754.58   475.5  755.74   503.5  761.44   519.5  765.56
   559.4  778.18  568.41779.5629   579.4  779.72   583.4  780.46   587.4  782.68
#Mann= 4 ,-1 , 0
       0     .12       0  381.61    .045       0   415.9     .12       0
  568.41    .016       0
#XS Ineff= 2 , 0
           196.9  750.05
Permanent Ineff=
       F       F
Bank Sta=381.61,415.9
XS Rating Curve= 0 ,0
Exp/Cntr=0.3,0.1

Type RM Length L Ch R = 1 ,12987.2 ,337.9,339.7,341.3
XS GIS Cut Line= 3
     2332095.937      364463.783     2332520.375      364445.843
     2332657.584      364398.123
#Sta/Elev= 30
       0  802.77    39.7  785.51    83.4  763.05    95.3  757.62   111.2  751.02
   123.1  747.77   158.8  745.59   234.2  746.01   254.1  744.43     274  745.77
   277.9  745.05   280.2  743.79   285.9   740.8   289.8  740.58   297.8     741
   313.6  743.86   357.3  743.56   365.3  744.73   377.2  747.67   389.1  749.19
   420.8  750.17   436.6  751.84   515.1  764.39     523     766   530.8  769.61
  537.31770.4178  548.15770.4993   554.4  770.97   562.2  772.92   570.1  773.96
#Mann= 5 ,-1 , 0
       0     .12       0   280.2    .045       0   313.6     .12       0
  537.31    .016       0  548.15     .12       0
Bank Sta=280.2,313.6
XS Rating Curve= 0 ,0
Exp/Cntr=0.3,0.1

Type RM Length L Ch R = 1 ,12647.5 ,373.4,372.5,371.8
XS GIS Cut Line= 3
     2332114.643      364742.321      2332537.82      364753.172
       2332691.9      364685.897
#Sta/Elev= 30
       0  801.46    43.9  782.46    71.9  768.79   107.8   748.8   119.8   743.8
   143.8  741.98   159.7  743.26   211.7  744.05   223.6  741.94   239.6  743.12
   255.6  741.93   265.7  740.36   283.5  739.17   295.7 740.594   299.5  740.86
   311.5  745.13   423.3  749.87     435  751.19   462.4  752.82   474.2   753.1
   485.9  752.19   501.5  754.34   517.2  755.45   528.9  754.93  551.51759.9935
   564.1  762.95   579.7  763.16   583.6  764.16  586.75766.5911   591.4  769.51
#Mann= 5 ,-1 , 0
       0     .12       0   265.7    .045       0   295.7     .12       0
  551.51    .016       0  586.75     .12       0
Bank Sta=265.7,295.7
XS Rating Curve= 0 ,0
Exp/Cntr=0.3,0.1

Type RM Length L Ch R = 1 ,12275   ,437,438.7,440.1
XS GIS Cut Line= 3
     2332158.696      365111.027     2332642.701      365103.667
     2332737.708       365083.11
#Sta/Elev= 30
       0  814.68    39.7  794.55   103.2  761.22     119  752.11     127  746.48
   134.9   740.2   138.9  738.25   146.8  736.14   150.8     736   166.6  736.69
   170.6  737.33   174.4738.9165   178.6  740.42   186.5   741.4   206.3  739.46
  219.15738.9915   230.1   738.7     246  739.52   265.8  739.66  282.46739.1248
  311.81739.0396   349.2  739.76   400.7  741.57   503.5   742.6  513.94743.2535
   530.7  743.38   542.4  744.73     554  746.82   565.7  749.69   581.3  754.69
#Mann= 7 ,-1 , 0
       0     .12       0   138.9    .045       0   174.4     .12       0
  219.15     .06       0  282.46     .12       0  311.81     .06       0
  513.94     .12       0
Bank Sta=138.9,174.4
XS Rating Curve= 0 ,0
Exp/Cntr=0.3,0.1

Type RM Length L Ch R = 1 ,11836.3 ,590.6,592.3,594
XS GIS Cut Line= 2
     2332159.489      365510.859     2332687.852      365535.848
#Sta/Elev= 30
       0  808.42    27.8  793.78   115.3  750.06   119.3  747.81   131.2  740.01
   135.2  738.31   139.2  737.46   143.2  737.25   159.1  737.63     171  735.56
     175  735.41   190.9   735.8   214.8  737.48   226.7  736.86   246.6  737.38
   258.5  735.92   274.4  733.97   286.4   734.5   290.3  735.13   293.2735.9783
   298.3  737.55   302.3  737.93   314.2  737.04  334.92737.1179   373.8  737.77
   405.7  737.21   433.5  738.02   497.1  743.36     513  745.28     529  748.27
#Mann= 4 ,-1 , 0
       0     .12       0   258.5    .045       0   293.2     .12       0
  334.92     .06       0
#XS Ineff= 2 , 0
          155.42  739.32  413.62          739.73
Permanent Ineff=
       F       F
Bank Sta=258.5,293.2
XS Rating Curve= 0 ,0
Exp/Cntr=0.3,0.1

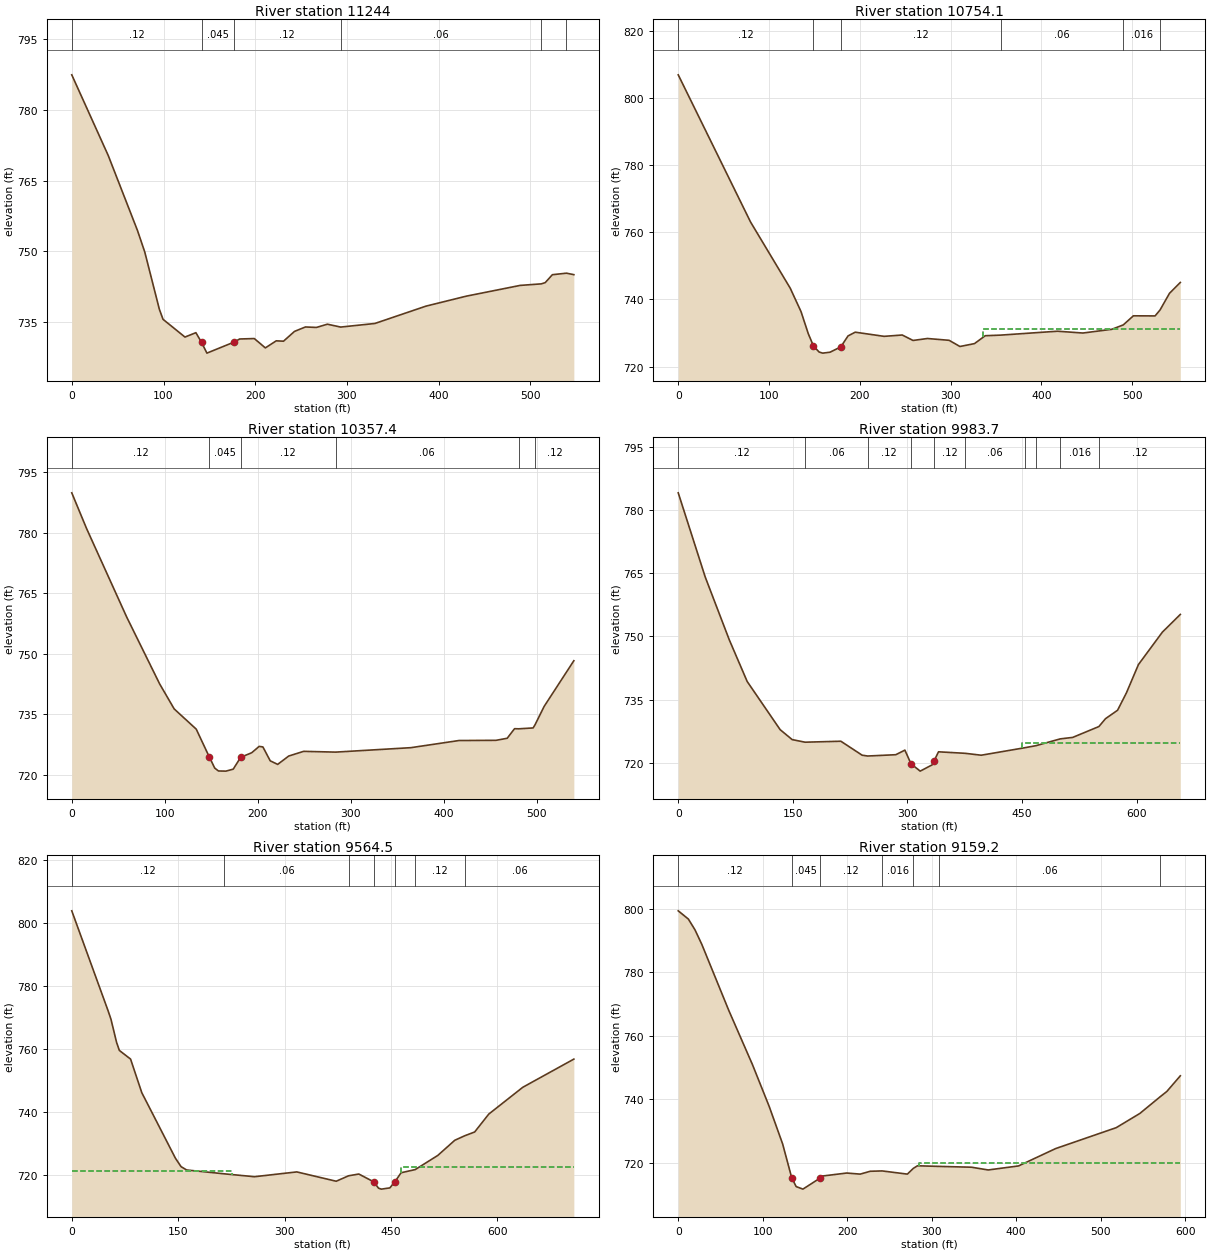
Type RM Length L Ch R = 1 ,11244   ,491.3,489.9,488.4
XS GIS Cut Line= 3
     2332129.679      365938.904     2332580.137      365993.406
     2332653.922      366050.915
#Sta/Elev= 30
       0  787.44    39.8   770.3    71.6  754.43    79.6  749.83    95.5  737.68
    99.5  735.56   123.4   731.8   135.3  732.73  141.46  730.67   147.3  728.39
   176.3 730.684   183.1  731.39     199  731.48     211   729.5   222.9     731
   230.8  730.92   242.8     733   254.7  733.94   266.7  733.84   278.6  734.53
  293.11733.9194   330.4  734.68   386.1  738.36   429.9  740.47   488.8  742.76
  511.76743.0845   516.1  743.35   523.9  745.03  539.25745.3536   547.3  745.04
#Mann= 6 ,-1 , 0
       0     .12       0  141.46    .045       0   176.3     .12       0
  293.11     .06       0  511.76    .016       0  539.25     .08       0
Bank Sta=141.46,176.3
XS Rating Curve= 0 ,0
Exp/Cntr=0.3,0.1

Type RM Length L Ch R = 1 ,10754.1 ,402.3,396.7,391.1
XS GIS Cut Line= 2
      2332075.58      366381.861     2332627.432      366420.729
#Sta/Elev= 30
       0  806.82    79.6  763.08   123.4  743.35   135.3  736.38   143.3   729.8
     149  726.17   155.2  724.36   159.2  724.03   167.2   724.3   179.1  725.88
   187.1  729.15     195  730.26   226.9  729.02   246.8  729.42   258.7   727.8
   274.6  728.38   298.5  727.84   310.4     726   326.4  726.86   338.3  729.21
  355.43  729.39   417.9  730.55   445.8  730.01   477.6  731.11  490.33732.4202
   501.5  735.13   525.4   735.1  530.84736.8539   541.3  741.83   553.2  745.05
#Mann= 6 ,-1 , 0
       0     .12       0     149    .045       0   179.1     .12       0
  355.43     .06       0  490.33    .016       0  530.84     .12       0
#XS Ineff= 2 , 0
                          336.22          731.32
Permanent Ineff=
       F       F
Bank Sta=149,179.1
XS Rating Curve= 0 ,0
Exp/Cntr=0.3,0.1

Type RM Length L Ch R = 1 ,10357.4 ,376.5,373.7,370.8
XS GIS Cut Line= 4
     2332072.506      366787.803     2332198.374      366793.012
     2332500.023      366738.758     2332607.662      366737.022
#Sta/Elev= 30
       0  789.85    15.8  781.07      59  759.12    94.5  742.53   110.2  736.31
   133.9  731.31   147.8 724.493   153.8  721.66   157.8  720.95   165.8  720.91
   173.7   721.4   181.7  724.33   193.6  725.47   201.6  727.04   205.6   726.9
   213.5  723.46   221.5  722.58   233.4  724.65   249.4  725.81  283.96725.6203
   364.8  726.72   416.5  728.49   456.4  728.54   468.4  729.05   476.3  731.42
  480.85 731.391   496.3  731.61  498.45732.4369   508.2  736.96   540.1  748.26
#Mann= 6 ,-1 , 0
       0     .12       0   147.8    .045       0   181.7     .12       0
  283.96     .06       0  480.85    .016       0  498.45     .12       0
Bank Sta=147.8,181.7
XS Rating Curve= 0 ,0
Exp/Cntr=0.3,0.1

Type RM Length L Ch R = 1 ,9983.7  ,399.5,419.2,438.9
XS GIS Cut Line= 4
     2332048.634      367112.022     2332189.259      367190.147
     2332524.329      367084.244      2332666.69      367110.286
#Sta/Elev= 30
       0  784.11    35.3  764.12    66.7  749.24    90.2   739.3   133.4  727.84
   149.1  725.49  165.96724.8726   212.8   725.1   240.7  721.78  247.92721.5898
   284.7   721.9   296.6  722.99   304.6  719.74   316.6     718   332.6  719.52
   334.6  720.37   340.6  722.59  375.43722.2314   396.5  721.78  453.18723.5473
  468.29 724.054  499.93725.6597   516.2  726.01  550.45728.5878   559.2  730.47
   574.9  732.46   586.6  736.64   602.2  743.31   633.5  751.01     657  755.22
#Mann= 10 ,-1 , 0
       0     .12       0  165.96     .06       0  247.92     .12       0
   304.6    .045       0   334.6     .12       0  375.43     .06       0
  453.18     .12       0  468.29     .06       0  499.93    .016       0
  550.45     .12       0
#XS Ineff= 2 , 0
                          450.05          724.73
Permanent Ineff=
       F       F
Bank Sta=304.6,334.6
XS Rating Curve= 0 ,0
Exp/Cntr=0.3,0.1

Type RM Length L Ch R = 1 ,9564.5  ,414.9,405.3,395.8
XS GIS Cut Line= 4
     2331923.634      367348.133     2332065.995      367381.119
     2332378.495      367579.036     2332569.468      367596.397
#Sta/Elev= 30
       0  803.75    51.3  772.05    55.3  769.39    63.2  762.06    67.1  759.54
    82.9   756.8    98.7  746.17   146.1  725.42   154.1  722.73     162  721.68
  215.02720.4638   257.5  719.55   317.2  721.07   372.8  718.12  390.27719.8461
   404.7   720.4   425.6717.9402   432.5  715.91   436.5  715.62   448.4  716.01
   455.6 717.966   464.3  720.81  484.16721.8062     516  726.29     540   731.1
  554.07732.5256     568  733.72   587.9  739.39   635.9  747.88   707.8  756.79
#Mann= 7 ,-1 , 0
       0     .12       0  215.02     .06       0  390.27     .12       0
   425.6    .045       0   455.6    .016       0  484.16     .12       0
  554.07     .06       0
#XS Ineff= 2 , 0
          225.39  721.49  463.98           722.7
Permanent Ineff=
       F       F
Bank Sta=425.6,455.6
XS Rating Curve= 0 ,0
Exp/Cntr=0.3,0.1

Type RM Length L Ch R = 1 ,9159.2  ,223.7,231,238.3
XS GIS Cut Line= 2
     2331871.551      367761.328      2332456.62      367865.494
#Sta/Elev= 30
       0  799.46      12  796.86    19.9  793.43    27.9  788.88    59.8  768.04
    87.7  751.01   107.7  737.68   123.6  725.85   134.4  715.11   139.6   712.4
   147.6   711.6   167.5  715.02   171.5  715.76   199.4  716.68   215.4  716.34
   227.3  717.24  241.42 717.346   271.2  716.34   278.3718.1575   283.2  718.97
  308.37718.7778     347  718.52   366.9  717.65   402.8  718.92   446.7   724.4
   518.5  731.01   546.4  735.49  570.29740.7281   578.3  742.42   594.3  747.37
#Mann= 7 ,-1 , 0
       0     .12       0   134.4    .045       0   167.5     .12       0
  241.42    .016       0   278.3     .12       0  308.37     .06       0
  570.29     .12       0
#XS Ineff= 2 , 0
                          285.45          719.93
Permanent Ineff=
       F       F
Bank Sta=134.4,167.5
XS Rating Curve= 0 ,0
Exp/Cntr=0.3,0.1

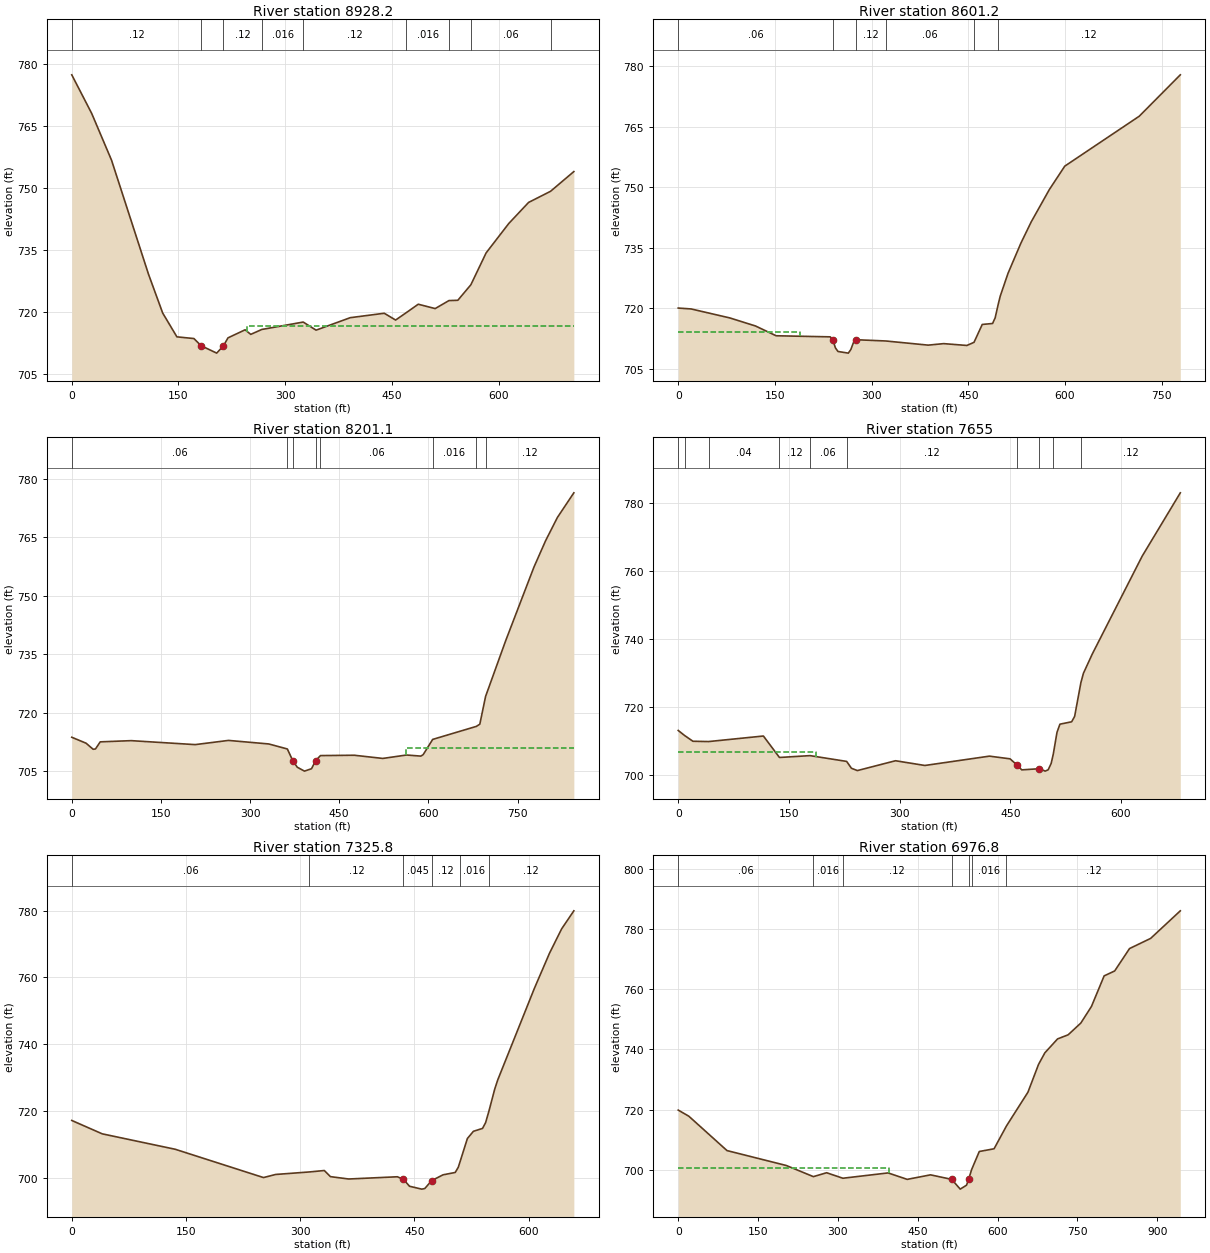
Type RM Length L Ch R = 1 ,8928.2  ,325.8,327,327.8
XS GIS Cut Line= 3
     2331795.162      367917.578     2332170.162      368122.439
     2332435.787      368039.105
#Sta/Elev= 30
       0  777.32      28     768    55.9   756.7   107.8  729.19   127.8  719.78
   147.8  714.03   171.7  713.62   181.8  711.89   203.7   710.1  213.23  711.88
   219.6  713.79   243.6  715.73   251.6  714.63  267.14715.8161  325.29717.6035
   343.4  715.65   391.4  718.66   439.2  719.73   455.2  718.09  470.19719.8754
     487  721.91   510.8  720.86  530.17722.7926   542.6  722.86  560.95726.6089
   582.4  734.31   614.2   741.4   642.1   746.5  672.95 749.186   705.7  753.95
#Mann= 9 ,-1 , 0
       0     .12       0   181.8    .045       0  213.23     .12       0
  267.14    .016       0  325.29     .12       0  470.19    .016       0
  530.17     .12       0  560.95     .06       0  672.95     .12       0
#XS Ineff= 2 , 0
                          246.85          716.62
Permanent Ineff=
       F       F
Bank Sta=181.8,213.23
XS Rating Curve= 0 ,0
Exp/Cntr=0.3,0.1

Type RM Length L Ch R = 1 ,8601.2  ,399.3,400.1,400.6
XS GIS Cut Line= 3
     2331573.559      368153.799     2332090.052      368466.299
     2332194.219      368607.358
#Sta/Elev= 30
       0  720.05      20  719.83      80  717.61   119.9  715.61   151.9  713.19
   235.9  712.92   239.8 712.179   243.9  710.18   247.9   709.3   263.9  708.89
   267.8  709.78   271.8  711.48   275.8  712.21  321.85   711.9   387.8  710.87
   411.8  711.24   447.8  710.79  458.91711.5621   471.7  715.99   487.7  716.23
   491.7  717.61  496.61721.0724   499.7  723.05   511.7  728.66   531.7  736.14
   547.7   741.4   575.7  749.37   599.7  755.19   715.3  767.56     779  777.81
#Mann= 6 ,-1 , 0
       0     .06       0   239.8    .045       0   275.8     .12       0
  321.85     .06       0  458.91    .016       0  496.61     .12       0
#XS Ineff= 2 , 0
          189.06  714.19
Permanent Ineff=
       F       F
Bank Sta=239.8,275.8
XS Rating Curve= 0 ,0
Exp/Cntr=0.3,0.1

Type RM Length L Ch R = 1 ,8201.1  ,533.4,546.1,558.7
XS GIS Cut Line= 3
     2331379.213      368427.769     2331902.825      368772.918
     2332113.924      368720.205
#Sta/Elev= 30
       0  713.64      24  712.12      36  710.55    39.9  710.64    47.9  712.46
    99.9  712.77   207.7  711.75   263.6  712.83   331.5  711.92  362.71710.6285
   371.9 707.602   379.4  705.94   391.5  704.94   403.4  705.56  410.36  707.65
   418.4708.9325   475.3  709.02   523.3   708.2   563.2  709.08   587.2   708.8
   591.2  709.17  607.19713.0881  680.59  716.43   686.5  716.99  696.21724.1307
     730  738.44   777.5  757.33   797.2  764.14     817   770.1   844.7  776.44
#Mann= 8 ,-1 , 0
       0     .06       0  362.71     .12       0   371.9    .045       0
  410.36     .12       0   418.4     .06       0  607.19    .016       0
  680.59     .08       0  696.21     .12       0
#XS Ineff= 2 , 0
                          562.44          710.81
Permanent Ineff=
       F       F
Bank Sta=371.9,410.36
XS Rating Curve= 0 ,0
Exp/Cntr=0.3,0.1

Type RM Length L Ch R = 1 ,7655    ,324.6,329.2,333.9
XS GIS Cut Line= 2
     2331215.486      368672.462     2331517.135      369282.271
#Sta/Elev= 30
       0  713.22    8.53711.7577    19.9  710.05   41.19709.9635   115.4  711.59
  137.17705.2875   178.5705.8323  228.18704.1346   234.7  702.12   242.7  701.44
   294.4  704.33   334.2  702.94   421.7  705.68   449.6  704.89   459.2  703.05
   465.5  701.65   489.4  701.99   497.3  701.28   501.3  701.68   505.3  703.53
  508.17706.2565   513.2  712.66   517.2  715.07   533.1  715.77   537.1  717.34
  545.56727.2303     549     730     561  735.66   628.6   764.4   680.3  783.01
#Mann= 10 ,-1 , 0
       0     .06       0    8.53     .08       0   41.19     .04       0
  137.17     .12       0   178.5     .06       0  228.18     .12       0
   459.2    .045       0   489.4     .12       0  508.17    .016       0
  545.56     .12       0
#XS Ineff= 2 , 0
          186.38  706.76
Permanent Ineff=
       F       F
Bank Sta=459.2,489.4
XS Rating Curve= 0 ,0
Exp/Cntr=0.3,0.1

Type RM Length L Ch R = 1 ,7325.8  ,348.2,349,349.8
XS GIS Cut Line= 2
     2330996.013      368744.294     2331162.679      369382.314
#Sta/Elev= 30
       0  717.19      40  713.18   135.9  708.56   251.8  700.09   267.8  701.02
  312.15701.7735   331.7   702.2   339.7  700.37   363.7  699.66   427.6  700.33
   435.6  699.55   443.6  697.49   459.6  696.63   463.6   696.8   472.8   699.2
   487.6  700.91   503.6  701.62   507.6  703.16  509.92704.8072   519.6  711.79
   527.5  713.94   539.5  714.81   543.5  716.52  547.72719.8475   555.5  726.58
   559.5  729.35   607.5  756.69   627.5  767.28   643.4  774.55   659.4  779.94
#Mann= 6 ,-1 , 0
       0     .06       0  312.15     .12       0   435.6    .045       0
   472.8     .12       0  509.92    .016       0  547.72     .12       0
Bank Sta=435.6,472.8
XS Rating Curve= 0 ,0
Exp/Cntr=0.3,0.1

Type RM Length L Ch R = 1 ,6976.8  ,428.2,403.9,371
XS GIS Cut Line= 3
     2330683.064      368812.684     2330806.761      369368.674
     2331179.157      369399.924
#Sta/Elev= 30
       0  719.87    19.9  717.84    91.6  706.43   203.1  701.47   253.9  697.78
   278.8  699.07  309.32697.2466   394.3  699.01   430.2  696.87     474  698.37
   513.8  696.87   529.8  693.63   541.7  694.94   545.7  696.94   551.1  700.06
   565.6  706.12   593.4  707.03  616.74714.6194     657   725.8   676.9  735.02
   688.8  738.88   712.7   743.5   732.6  744.87   756.4  748.77   776.3  754.26
   800.2  764.43     820  766.07   847.9   773.5   887.6  776.88   943.3  786.03
#Mann= 7 ,-1 , 0
       0     .06       0   253.9    .016       0  309.32     .12       0
   513.8    .045       0   545.7     .12       0   551.1    .016       0
  616.74     .12       0
#XS Ineff= 2 , 0
          396.28  700.68
Permanent Ineff=
       F       F
Bank Sta=513.8,545.7
XS Rating Curve= 0 ,0
Exp/Cntr=0.3,0.1

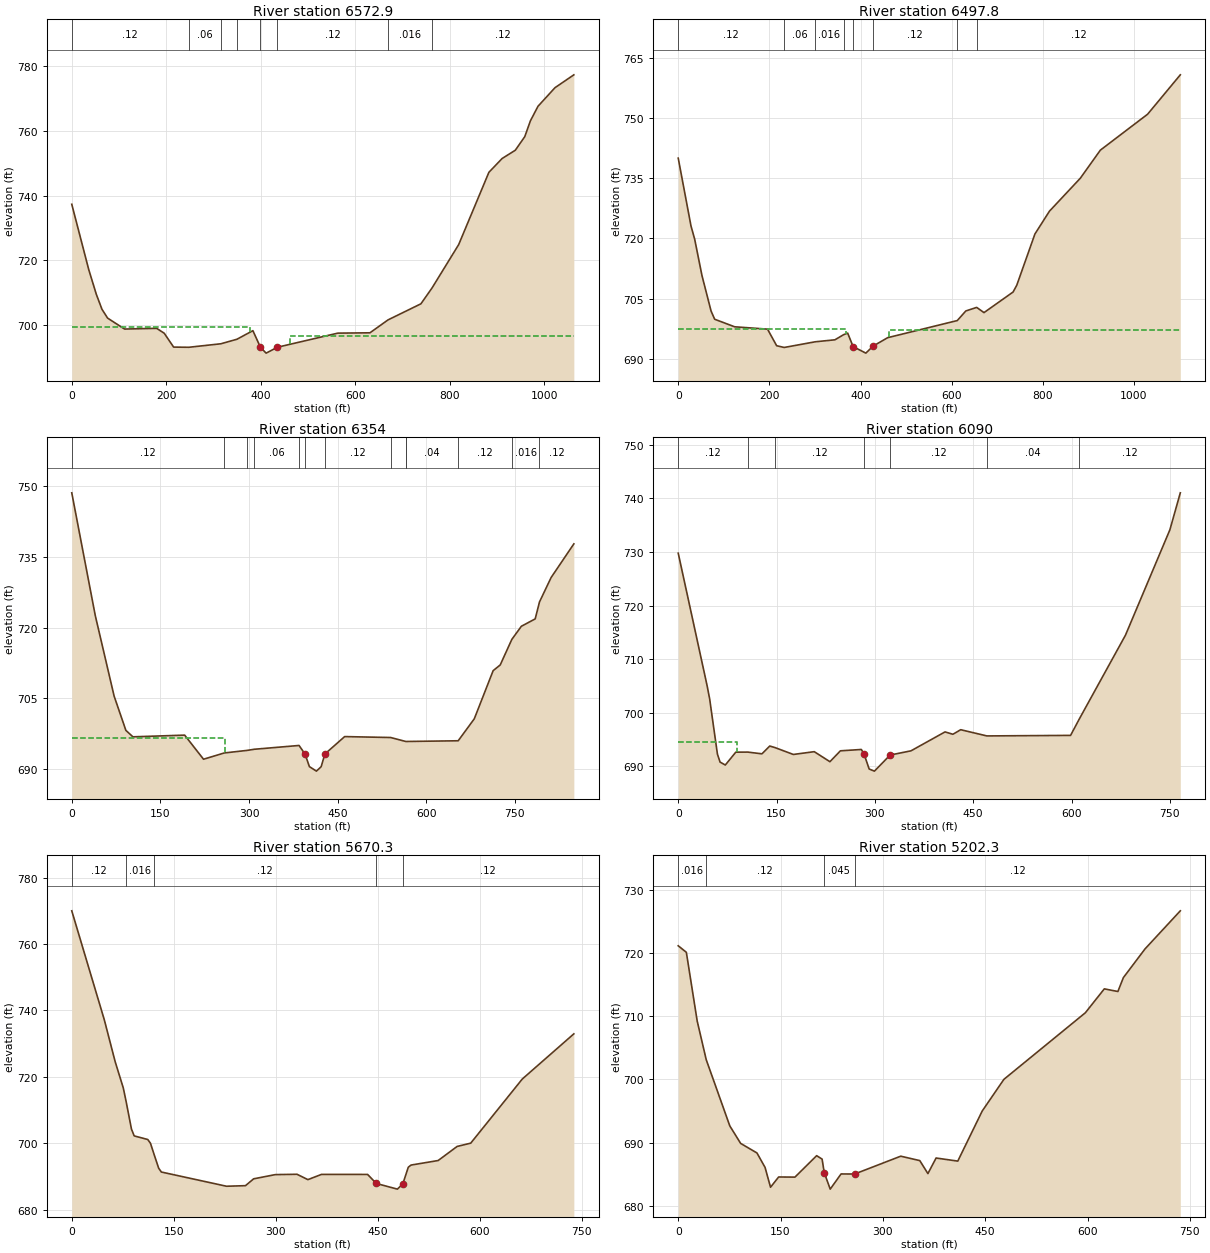
Type RM Length L Ch R = 1 ,6572.9  ,79.8,75.1,73.7
XS GIS Cut Line= 3
     2330136.189      369125.184     2330401.322      369349.698
     2331114.053      369411.642
#Sta/Elev= 30
       0  737.33    35.9  717.19    51.9  709.57    63.9  704.93    75.9  702.19
   111.8  698.82   179.7  699.04   195.7  697.53   215.6  693.25  247.71693.1947
  315.54694.2728  349.54695.6644   383.4  698.32   399.5 693.162   411.4  691.39
   435.4  693.21   563.2  697.56   631.2  697.66  669.57701.6533   739.1  706.61
  762.54711.4784     819  724.87     883  747.19     911  751.45   938.9     754
   958.9  758.19   970.9  763.08   986.9  767.56  1022.9   773.3  1062.8  777.27
#Mann= 8 ,-1 , 0
       0     .12       0  247.71     .06       0  315.54    .016       0
  349.54     .12       0   399.5    .045       0   435.4     .12       0
  669.57    .016       0  762.54     .12       0
#XS Ineff= 2 , 0
          377.71  699.43  461.92          696.72
Permanent Ineff=
       F       F
Bank Sta=399.5,435.4
XS Rating Curve= 0 ,0
Exp/Cntr=0.3,0.1

Type RM Length L Ch R = 1 ,6497.8  ,127.1,143.9,160.9
XS GIS Cut Line= 3
     2330105.112       369162.25     2330383.353      369408.812
     2331109.105      369486.382
#Sta/Elev= 30
       0  739.98      28  723.08      36  719.83      52  710.76      72   701.9
      80  699.83   123.9  697.95   195.9  697.37   215.9  693.24  232.45   692.8
  300.51694.2144   343.8  694.71  362.97695.9936   371.8  696.37   383.7  693.02
   411.6  691.39   427.6  693.14   459.5  695.24  612.25 699.506     631   701.9
  654.75702.7863   670.9  701.49   734.7  706.62   742.7  708.29   782.6  721.08
   814.5  726.77   882.3  734.99   926.2  741.98  1029.9  750.94  1101.6  760.75
#Mann= 8 ,-1 , 0
       0     .12       0  232.45     .06       0  300.51    .016       0
  362.97     .12       0   383.7    .045       0   427.6     .12       0
  612.25    .016       0  654.75     .12       0
#XS Ineff= 2 , 0
          369.04  697.43  461.92          697.03
Permanent Ineff=
       F       F
Bank Sta=383.7,427.6
XS Rating Curve= 0 ,0
Exp/Cntr=0.3,0.1

Type RM Length L Ch R = 1 ,6354    ,268.4,264,259.5
XS GIS Cut Line= 4
     2330023.971      369238.773     2330369.261      369557.476
     2330661.095      369623.138     2330714.586      369683.658
#Sta/Elev= 30
       0  748.65    39.8  722.56    71.7  705.44    91.6  698.16   103.5  696.79
   191.1  697.15     223  692.03  258.12  693.36  297.28693.9142  309.06694.1484
   384.7 694.954   394.9693.1068   402.2  690.46   414.1   689.5   422.1  690.44
  428.45  693.14   461.9  696.84  539.72696.6447  564.89 695.816  565.71695.7994
  654.07695.9512   681.3  700.62   713.2  710.85   725.2  712.07  744.85717.4987
     761  720.29   784.4  721.86  791.62725.4415   811.3  730.64   849.8   737.8
#Mann= 13 ,-1 , 0
       0     .12       0  258.12    .016       0  297.28     .12       0
  309.06     .06       0   384.7     .12       0   394.9    .045       0
  428.45     .12       0  539.72     .06       0  564.89     .12       0
  565.71     .04       0  654.07     .12       0  744.85    .016       0
  791.62     .12       0
#XS Ineff= 2 , 0
          259.03  696.44
Permanent Ineff=
       F       F
Bank Sta=394.9,428.45
XS Rating Curve= 0 ,0
Exp/Cntr=0.3,0.1

Type RM Length L Ch R = 1 ,6090    ,421.2,419.7,418.2
XS GIS Cut Line= 3
      2329862.87      369521.744     2330383.704      369832.508
     2330475.718      369962.717
#Sta/Elev= 30
       0  729.76    43.9  705.12    47.9   702.6    59.8  692.26    63.8  690.78
    71.8  690.23    87.8  692.63  106.13692.6408   127.7  692.32   139.6  693.77
   147.4 693.493   175.6   692.2   207.5  692.72   231.4  690.85   247.4  692.88
   279.3  693.13   283.3  692.33   291.3  689.48   299.3  689.09   323.2  692.09
   355.1  692.88     407  696.41     419  695.97   430.9  696.82  470.81695.6597
   598.5  695.76  611.99 698.859   682.2  714.45     750  734.13   765.9  741.03
#Mann= 7 ,-1 , 0
       0     .12       0  106.13    .016       0   147.4     .12       0
   283.3    .045       0   323.2     .12       0  470.81     .04       0
  611.99     .12       0
#XS Ineff= 2 , 0
           89.99  694.54
Permanent Ineff=
       F       F
Bank Sta=283.3,323.2
XS Rating Curve= 0 ,0
Exp/Cntr=0.3,0.1

Type RM Length L Ch R = 1 ,5670.3  ,469.2,468,465.8
XS GIS Cut Line= 2
     2329675.266       369839.55     2330314.259      370209.244
#Sta/Elev= 30
       0  769.98    47.9  737.14    63.8  724.58    75.8  716.63   79.86712.6439
    87.8  704.26    91.8  702.23   111.7  701.15   115.7  700.02  121.18696.5725
   127.7  692.54   131.7  691.36   227.5  687.08   255.4  687.25   267.4  689.31
   299.3  690.58   331.2  690.68   347.2  689.07   367.1  690.64     435  690.63
   447.8 687.907   478.8  686.21   486.8  687.82   494.8   692.8   498.8  693.45
   538.7  694.82   566.6  699.06   586.6  700.05   662.4  719.35   738.2  732.95
#Mann= 5 ,-1 , 0
       0     .12       0   79.86    .016       0  121.18     .12       0
   447.8    .045       0   486.8     .12       0
Bank Sta=447.8,486.8
XS Rating Curve= 0 ,0
Exp/Cntr=0.3,0.1

Type RM Length L Ch R = 1 ,5202.3  ,535.9,528.5,520.1
XS GIS Cut Line= 2
     2329491.343       370210.98     2330177.106      370478.342
#Sta/Elev= 30
       0  721.13    11.9   720.1    27.8  709.23   41.04703.1157    75.6  692.65
    91.5  689.88   115.4  688.37   127.3  686.08   135.3  682.95   147.2  684.57
   171.1  684.55   202.9  687.94   210.9   687.4     214  685.27   222.8  682.65
   238.7  685.05   258.6  685.04   326.2  687.86   354.1  687.16     366  685.11
     378  687.57   409.8  687.08   445.6     695   477.4  700.01   596.8  710.54
   624.6  714.32   644.5   713.9   652.5  716.09   684.3  720.64     736  726.66
#Mann= 4 ,-1 , 0
       0    .016       0   41.04     .12       0     214    .045       0
   258.6     .12       0
Bank Sta=214,258.6
XS Rating Curve= 0 ,0
Exp/Cntr=0.3,0.1

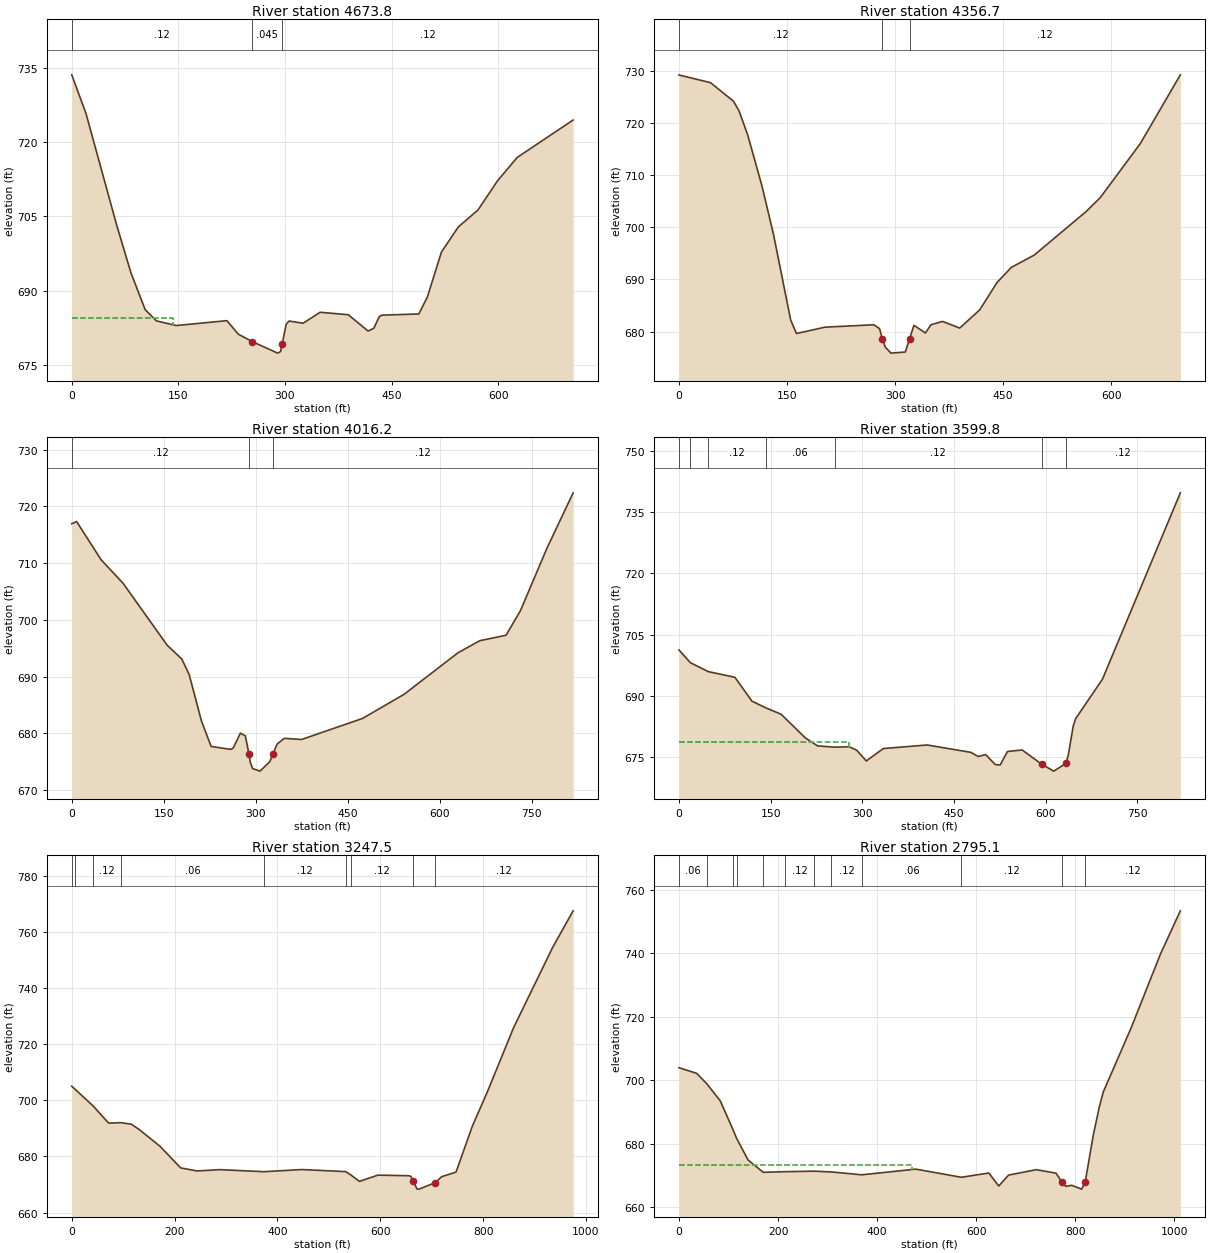
Type RM Length L Ch R = 1 ,4673.8  ,317.7,317,316.3
XS GIS Cut Line= 3
     2329369.815        370639.8      2329925.37      370662.369
     2330064.259      370717.925
#Sta/Elev= 30
       0  733.56    19.9  725.84    63.5  703.13    83.4  693.61   103.3  686.22
   119.2  683.94     147     683   218.4  683.99   234.3  681.27   254.2  679.75
   289.9  677.44   293.9  677.77   296.1679.2605   301.8  683.28   305.8  683.91
   325.7  683.47   349.5  685.68   389.2  685.18     417   681.9     425  682.44
   432.9  684.83   436.9   685.1   488.5  685.34   500.4  688.74   520.3  697.83
   544.1   702.9   571.8  706.33   599.3  712.22   626.9   716.9   705.6  724.45
#Mann= 3 ,-1 , 0
       0     .12       0   254.2    .045       0   296.1     .12       0
#XS Ineff= 2 , 0
          142.83  684.54
Permanent Ineff=
       F       F
Bank Sta=254.2,296.1
XS Rating Curve= 0 ,0
Exp/Cntr=0.3,0.1

Type RM Length L Ch R = 1 ,4356.7  ,336,340.5,344.8
XS GIS Cut Line= 2
     2329322.619      370939.606     2330017.384      370981.814
#Sta/Elev= 30
       0  729.22    43.8  727.75    75.6  724.21    83.5  722.32    95.5   717.7
   115.3  707.91   131.2  698.69   155.1  682.22   163.1  679.62   202.8  680.84
   270.5   681.3   278.4  680.57   282.4  678.58   286.4  677.02   294.3  675.86
   314.2  676.07  320.24  678.64   326.2   681.2   342.1  679.73     350  681.32
   365.9  681.94   389.8  680.67   417.6  684.17   441.5   689.4   461.4  692.31
   493.2  694.67   564.8  702.97   584.7  705.67   640.4  716.05     696  729.25
#Mann= 3 ,-1 , 0
       0     .12       0   282.4    .045       0  320.24     .12       0
Bank Sta=282.4,320.24
XS Rating Curve= 0 ,0
Exp/Cntr=0.3,0.1

Type RM Length L Ch R = 1 ,4016.2  ,413.3,416.5,419.4
XS GIS Cut Line= 4
     2329241.889      371062.002     2329356.473      371205.231
     2329812.202      371319.814     2329908.556      371452.627
#Sta/Elev= 30
       0  716.93       8  717.31    47.8  710.59    83.7  706.44   155.5  695.54
   179.4   693.1   191.4  690.38   211.3  682.25   227.2   677.7   259.1  677.18
   263.1  677.39     275  680.05     283  679.56  289.03  676.35     291  674.93
   294.9   673.8   306.9  673.35   322.8     675     328 676.323   334.8  678.12
   346.7  679.13   374.6  678.92   474.1  682.63   541.8  686.88   629.4  694.17
   665.1  696.32     708  697.28   731.5  701.62   774.4  712.54   817.4  722.37
#Mann= 3 ,-1 , 0
       0     .12       0  289.03    .045       0     328     .12       0
Bank Sta=289.03,328
XS Rating Curve= 0 ,0
Exp/Cntr=0.3,0.1

Type RM Length L Ch R = 1 ,3599.8  ,352.9,352.3,351.6
XS GIS Cut Line= 3
     2329035.303      371327.841     2329160.081      371493.026
     2329730.369      371719.119
#Sta/Elev= 30
       0  701.25   18.73698.1187   48.08695.9297    91.6  694.55   119.4  688.71
  142.14687.0693   167.2   685.5     207  679.69   226.9  677.76  254.98677.4509
   278.7  677.54   290.7  676.72   306.6  674.07   334.5  677.11   406.2  677.98
   477.9  676.17   489.8  675.14   501.8  675.64   517.7  673.18   525.7  673.08
   537.6  676.38   561.6  676.76   593.4   673.3   613.3  671.58   633.3  673.46
   637.2  675.53   645.2  682.59   649.2  684.43     693  694.06   820.5  739.69
#Mann= 7 ,-1 , 0
       0     .12       0   18.73     .06       0   48.08     .12       0
  142.14     .06       0  254.98     .12       0   593.4    .045       0
   633.3     .12       0
#XS Ineff= 2 , 0
          277.61  678.75
Permanent Ineff=
       F       F
Bank Sta=593.4,633.3
XS Rating Curve= 0 ,0
Exp/Cntr=0.3,0.1

Type RM Length L Ch R = 1 ,3247.5  ,452.4,452.4,452.3
XS GIS Cut Line= 2
     2328655.952      371676.585     2329579.884      371988.758
#Sta/Elev= 30
       0  705.02    6.94703.8855   41.47 698.024    71.9  691.88   95.57692.0377
   115.9  691.51   131.9  689.52   171.9  683.61   211.8  675.95   243.8  674.85
   287.8  675.32  373.93 674.591   447.6  675.35  532.86674.6176  542.69673.4424
   559.6  671.14   595.5  673.37   655.5  673.15   659.5  672.96   664.6671.1115
   671.5  668.43   675.5  668.38   707.4  670.71   719.4  672.81   747.4  674.44
   779.4  690.92   807.4  702.59   859.3  725.84   935.3  754.44   975.2  767.49
#Mann= 9 ,-1 , 0
       0     .12       0    6.94     .06       0   41.47     .12       0
   95.57     .06       0  373.93     .12       0  532.86     .08       0
  542.69     .12       0   664.6    .045       0   707.4     .12       0
Bank Sta=664.6,707.4
XS Rating Curve= 0 ,0
Exp/Cntr=0.3,0.1

Type RM Length L Ch R = 1 ,2795.1  ,667.3,666.1,666.7
XS GIS Cut Line= 2
     2328533.556      372085.439     2329494.494      372403.148
#Sta/Elev= 30
       0  703.92    35.9  702.14   56.54698.8076    83.7  693.41  110.02684.0651
  116.42 681.683   139.5  674.86  170.08670.9665  214.72671.1688  273.08671.3267
  307.83671.0794  369.09670.1823   478.2  671.97  570.09669.4015   625.6  670.74
   645.5  666.66   665.4  670.08   721.2   671.8   761.1   670.7     773  667.92
     781  666.55   792.9  666.87   812.9  665.67  820.14     668   836.8  683.02
   848.7  691.64   856.7  696.34   912.5  716.35   972.2  739.81  1012.1  753.34
#Mann= 12 ,-1 , 0
       0     .06       0   56.54     .12       0  110.02     .06       0
  116.42     .12       0  170.08     .06       0  214.72     .12       0
  273.08     .06       0  307.83     .12       0  369.09     .06       0
  570.09     .12       0     773    .045       0  820.14     .12       0
#XS Ineff= 2 , 0
          470.59  673.34
Permanent Ineff=
       F       F
Bank Sta=773,820.14
XS Rating Curve= 0 ,0
Exp/Cntr=0.3,0.1