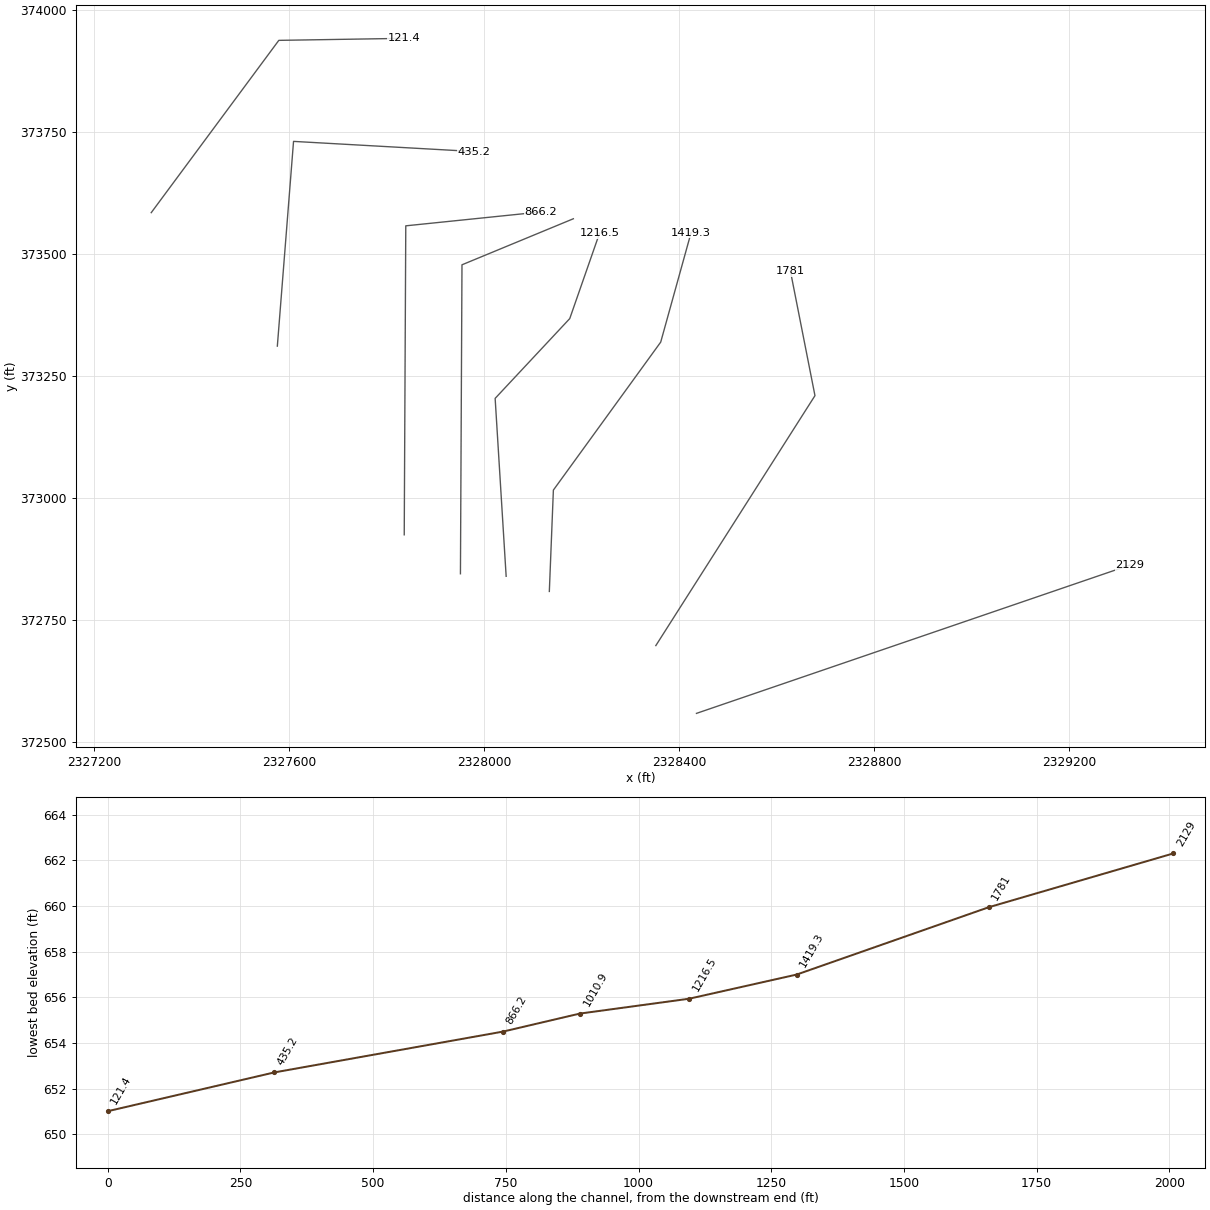
HEC-RAS study SFKSLPYCRK.prj: SFKSLPYCRK

--- SFKSLPYCRK.g01 (geometry) --- (continued)

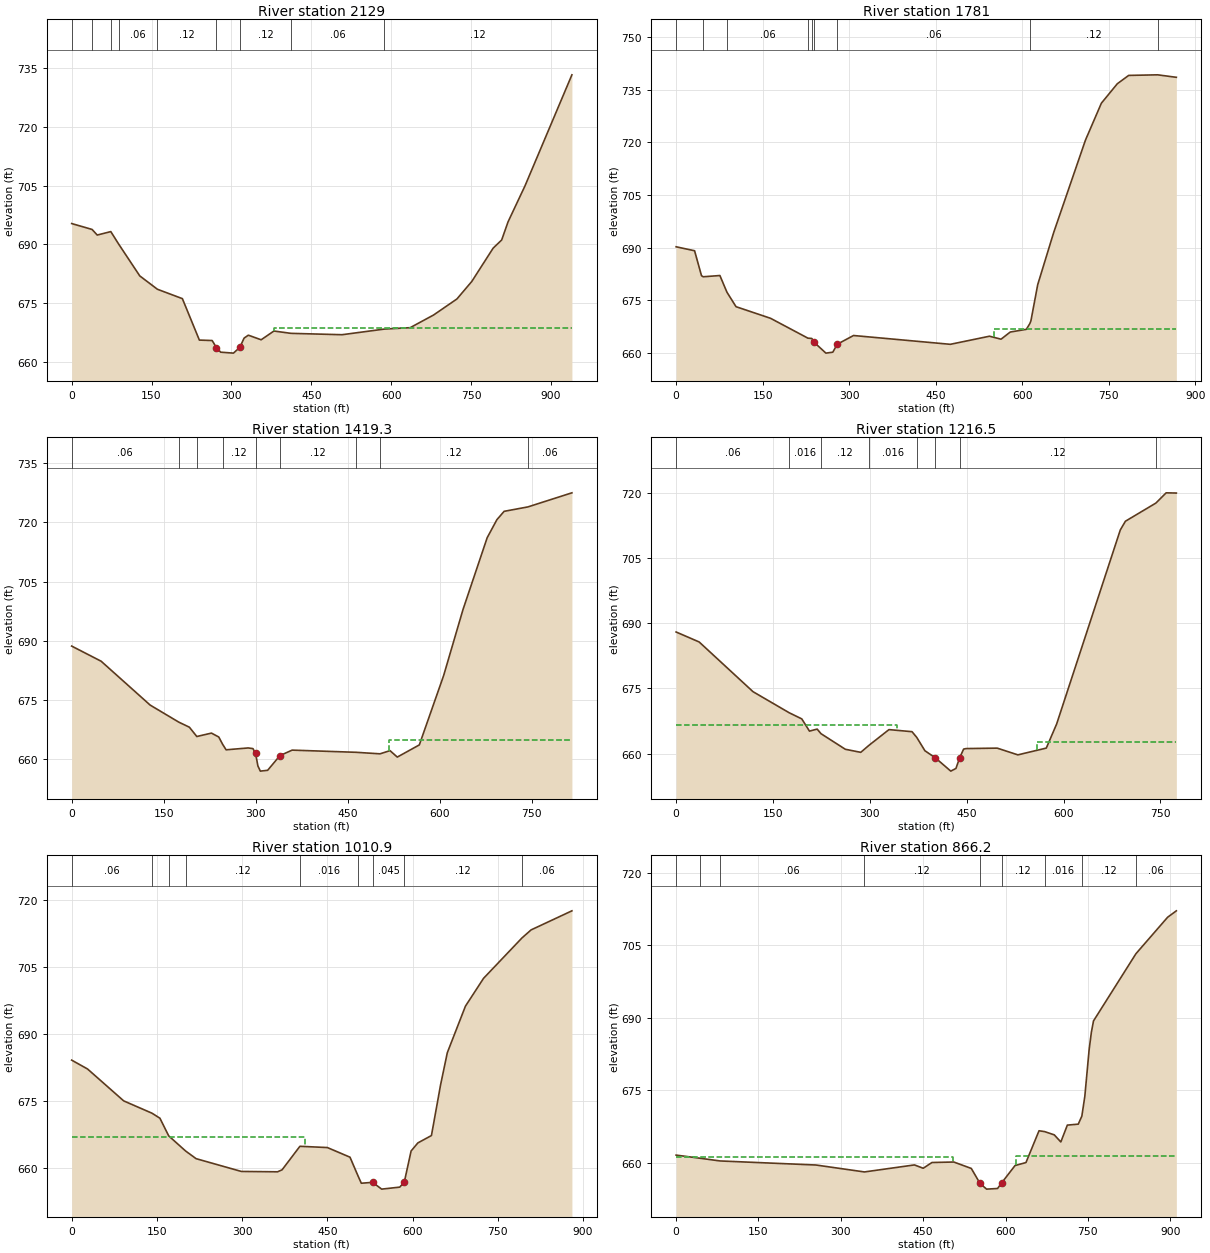
Type RM Length L Ch R = 1 ,2129    ,333.3,348,363.1
XS GIS Cut Line= 2
     2328435.787      372558.203     2329324.676      372862.022
#Sta/Elev= 30
       0  695.32   38.33693.8185      48  692.39   73.46693.2698   88.32 690.076
   127.9  681.98  161.04678.5789   207.9  676.19   239.8  665.63   263.8  665.52
   271.8  663.72   279.8  662.55   303.8  662.31   315.8  663.78   323.8  666.14
   331.8  666.88   355.8  665.71   379.8  667.94  411.78667.3488   507.7     667
  587.45668.4419   635.6  668.79   679.6  672.02   723.5  676.11   751.5  680.59
   791.5  689.06   807.5  691.13   819.5  695.76   851.4  704.95   939.4  733.21
#Mann= 9 ,-1 , 0
       0     .06       0   38.33    .016       0   73.46     .12       0
   88.32     .06       0  161.04     .12       0   271.8    .045       0
   315.8     .12       0  411.78     .06       0  587.45     .12       0
#XS Ineff= 2 , 0
                          379.77          668.65
Permanent Ineff=
       F       F
Bank Sta=271.8,315.8
XS Rating Curve= 0 ,0
Exp/Cntr=0.3,0.1

Type RM Length L Ch R = 1 ,1781    ,359.6,361.7,361.5
XS GIS Cut Line= 3
     2328352.454      372697.092     2328678.843      373209.244
     2328628.495      373464.453
#Sta/Elev= 30
       0  690.25      32  689.12      44  682.02   46.92681.7061    75.9  682.06
   88.15 677.305   103.9  673.18   163.8  669.87  228.51664.2162  235.31664.1266
   239.7  662.98   259.7  659.95   271.7  660.22   279.4662.4875   307.6  664.97
   475.5  662.46   543.4  664.77   563.4  663.92   579.4  665.96   607.3  666.73
  613.39668.3835   615.2  669.14     627  679.46   654.6  694.27   709.8  720.65
   737.4  731.17     765   736.7   784.7  739.08  834.92739.2476   867.4  738.54
#Mann= 9 ,-1 , 0
       0     .12       0   46.92    .016       0   88.15     .06       0
  228.51     .12       0  235.31     .06       0   239.7    .045       0
   279.4     .06       0  613.39     .12       0  834.92     .06       0
#XS Ineff= 2 , 0
                          551.08          666.86
Permanent Ineff=
       F       F
Bank Sta=239.7,279.4
XS Rating Curve= 0 ,0
Exp/Cntr=0.3,0.1

Type RM Length L Ch R = 1 ,1419.3  ,205.5,202.8,199.9
XS GIS Cut Line= 4
     2328134.013      372808.059      2328142.32      373015.734
     2328362.456      373318.939     2328424.758      373543.228
#Sta/Elev= 30
       0  688.67      48  684.84   127.9  673.73  174.42669.4232   191.8  668.13
  203.94 665.769   227.8  666.63   239.7  665.65  246.09663.7835   251.7   662.4
   287.6  662.87   295.5   662.7   299.7661.4835   303.5  658.32   307.5     657
   319.4  657.21   339.4  660.93   359.3  662.32  463.59661.7664  502.64661.3832
   518.8  662.19   530.7  660.56   566.6  663.64   606.2  681.19   637.8  697.93
   677.2  716.12     693  720.68   704.8   722.8  743.69723.9278   815.3  727.49
#Mann= 9 ,-1 , 0
       0     .06       0  174.42     .12       0  203.94    .016       0
  246.09     .12       0   299.7    .045       0   339.4     .12       0
  463.59     .06       0  502.64     .12       0  743.69     .06       0
#XS Ineff= 2 , 0
                          517.03             665
Permanent Ineff=
       F       F
Bank Sta=299.7,339.4
XS Rating Curve= 0 ,0
Exp/Cntr=0.3,0.1

Type RM Length L Ch R = 1 ,1216.5  ,138.5,205.6,226.5
XS GIS Cut Line= 4
     2328045.448      372839.073     2328022.878      373203.656
     2328175.888       373367.14     2328236.999       373542.14
#Sta/Elev= 30
       0  688.01    35.7  685.71   119.1  674.25  174.89669.4119   194.6  667.98
   206.5  665.16   218.4  665.63  224.35  664.57     262  660.98   285.9  660.27
   298.4661.8615   329.6  665.51   365.3  665.03  372.63 663.709   385.3  660.63
   401.3  659.02   425.3  655.94   433.3  656.56   439.2  659.06   445.2  661.02
   449.2  661.14   497.2  661.24   529.2  659.69   573.2  661.25   589.2  666.79
   687.8  711.53   695.7  713.54  742.94717.7324   758.8  720.09   774.6  720.04
#Mann= 8 ,-1 , 0
       0     .06       0  174.89    .016       0  224.35     .12       0
   298.4    .016       0  372.63     .12       0   401.3    .045       0
   439.2     .12       0  742.94     .08       0
#XS Ineff= 2 , 0
           341.8  666.49  558.93           662.7
Permanent Ineff=
       F       F
Bank Sta=401.3,439.2
XS Rating Curve= 0 ,0
Exp/Cntr=0.3,0.1

Type RM Length L Ch R = 1 ,1010.9  ,190.9,144.8,145
XS GIS Cut Line= 3
     2327951.692      372844.241     2327954.847      373477.362
     2328183.295      373571.712
#Sta/Elev= 30
       0  684.18    27.9   682.2    91.6  675.05  141.23 672.301   155.3  671.17
  170.75667.2194  200.42663.8345     219  662.11   298.6  659.25   362.4  659.17
   370.3  659.62  401.63664.8816     450   664.6   489.8  662.44  503.88658.2579
   509.7  656.61   529.6  656.81   545.5  655.29   577.4  655.74   585.4   656.9
   597.3  663.83   609.2  665.64   633.1  667.29   649.1  678.59     661  685.83
   692.9  696.26   724.8   702.5  792.32711.5336   808.5  713.35   880.3  717.62
#Mann= 9 ,-1 , 0
       0     .06       0  141.23     .12       0  170.75    .016       0
  200.42     .12       0  401.63    .016       0  503.88     .12       0
   529.6    .045       0   585.4     .12       0  792.32     .06       0
#XS Ineff= 2 , 0
          410.73  666.91
Permanent Ineff=
       F       F
Bank Sta=529.6,585.4
XS Rating Curve= 0 ,0
Exp/Cntr=0.3,0.1

Type RM Length L Ch R = 1 ,866.2   ,435.2,430.9,426
XS GIS Cut Line= 3
     2327836.414      372924.102      2327839.57      373557.223
     2328115.934      373585.601
#Sta/Elev= 30
       0  661.54    43.9660.8882   79.87660.3333   254.8  659.49  343.01658.0568
     434  659.51     450  658.82   465.9  660.01   505.7  660.11   537.6  658.78
   553.5  655.67   565.4   654.5   585.4  654.63   593.3  655.86   617.2  659.38
   637.1     660   660.9  666.58  671.17666.4011   688.7  665.73   700.6  664.26
   712.5  667.75   732.4  667.95  738.88669.6088   744.3  673.69   752.2  683.42
   756.2  686.94   760.1  689.31  837.42703.2276   895.1  710.77     911   712.1
#Mann= 9 ,-1 , 0
       0     .12       0    43.9    .016       0   79.87     .06       0
  343.01     .12       0   553.5    .045       0   593.3     .12       0
  671.17    .016       0  738.88     .12       0  837.42     .06       0
#XS Ineff= 2 , 0
          504.64  661.11   619.2          661.35
Permanent Ineff=
       F       F
Bank Sta=553.5,593.3
XS Rating Curve= 0 ,0
Exp/Cntr=0.3,0.1

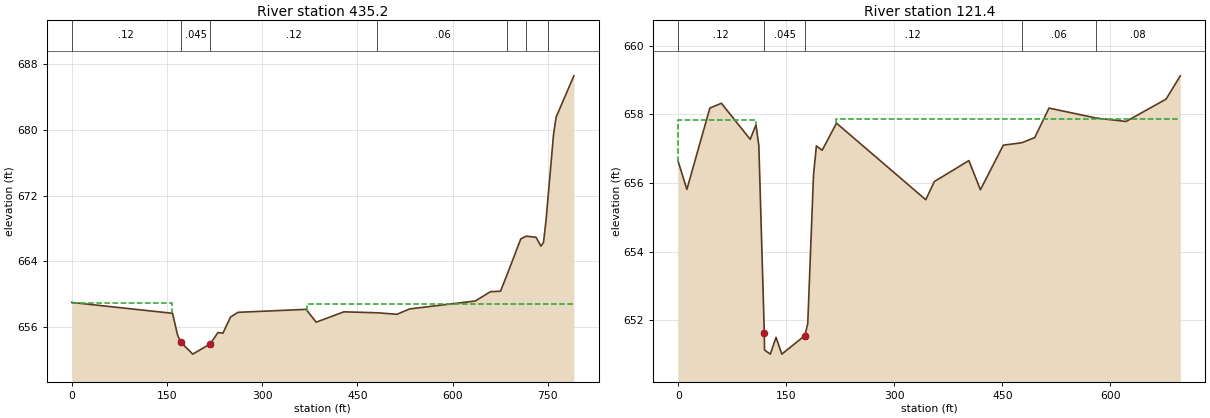
Type RM Length L Ch R = 1 ,435.2   ,327.7,313.8,299.5
XS GIS Cut Line= 3
     2327576.142      373310.753      2327609.37      373730.257
     2327979.031      373709.489
#Sta/Elev= 30
       0     659   158.8  657.68   166.7  655.04   171.7 654.175   190.6  652.71
   218.4  653.96   230.3  655.34   238.2  655.26   250.1  657.22     262   657.8
   369.2  658.16   385.1   656.6   428.8  657.86  481.53657.7422   512.4  657.56
   532.3  658.21   635.8  659.18   659.7  660.31   675.6  660.37  686.56662.5166
   707.5  666.74   716.1667.0682   731.4  666.94   739.3  665.86   743.3  666.31
   747.3     669  750.56671.9172   759.2  679.52   763.2  681.56   791.1  686.59
#Mann= 7 ,-1 , 0
       0     .12       0   171.7    .045       0   218.4     .12       0
  481.53     .06       0  686.56     .12       0   716.1    .016       0
  750.56     .12       0
#XS Ineff= 2 , 0
          157.69  658.92  370.69          658.78
Permanent Ineff=
       F       F
Bank Sta=171.7,218.4
XS Rating Curve= 0 ,0
Exp/Cntr=0.3,0.1

Type RM Length L Ch R = 1 ,121.4   ,124.4,121.4,118.4
XS GIS Cut Line= 3
     2327317.504      373584.208     2327579.175      373937.256
     2327836.692       373941.41
#Sta/Elev= 30
       0  656.62      12  655.81    43.9  658.18    59.9  658.32    99.9  657.27
   107.9  657.69   111.9  657.09   119.5  651.62   119.8  651.13   127.8  651.01
   135.8   651.5   143.8  651.01   175.8  651.55   179.8   651.9   187.8  656.23
   191.8  657.08   199.8  656.95   219.7  657.74   343.6  655.51   355.6  656.04
   403.5  656.65   419.5   655.8   451.3   657.1  476.68657.1679   494.9  657.32
   514.7  658.18  580.13657.8897   621.7  657.79   677.2  658.44     697  659.12
#Mann= 5 ,-1 , 0
       0     .12       0   119.5    .045       0   175.8     .12       0
  476.68     .06       0  580.13     .08       0
#XS Ineff= 2 , 0
          107.64  657.82  219.61          657.87
Permanent Ineff=
       F       F
Bank Sta=119.5,175.8
XS Rating Curve= 0 ,0
Exp/Cntr=0.3,0.1

Chan Stop Cuts=-1
Use User Specified Reach Order=0
Composite Channel Slope=5